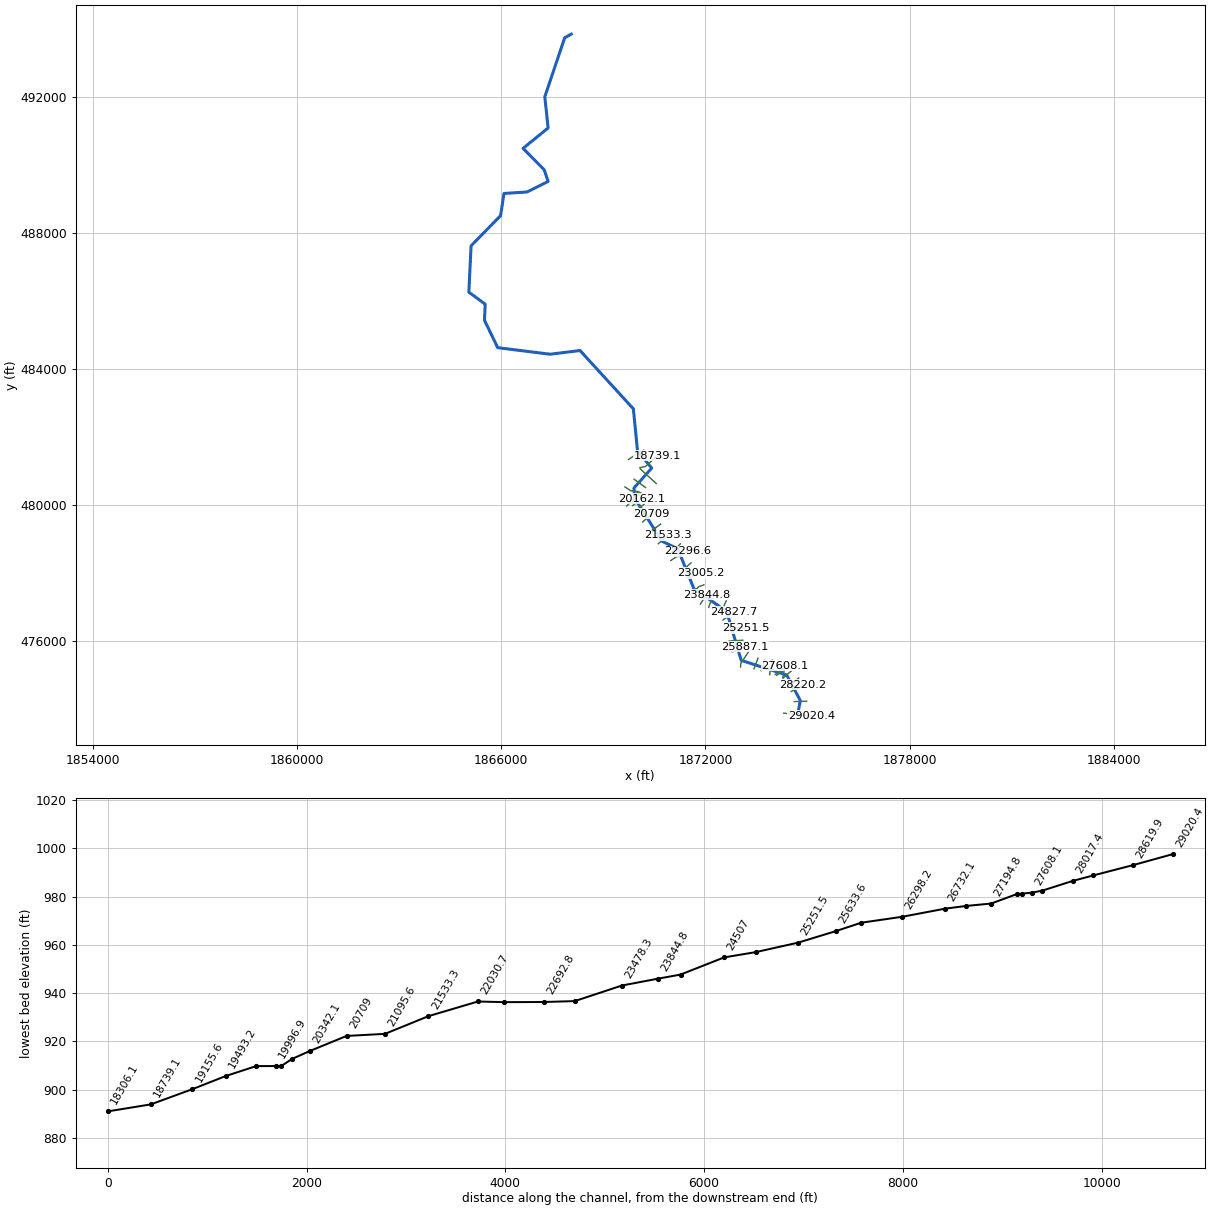
--- MORRISFK.prj (project) ---

Proj Title=MORRISFK
Current Plan=p01
Default Exp/Contr=0,0
English Units
Geom File=g01
Flow File=f01
Plan File=p01
BEGIN DESCRIPTION:
END DESCRIPTION:
DSS File=dss
DSS Export Rating Curves= 0
DSS Export Rating Curve Sorted= 0
DSS Export Volume Flow Curves= 0
DXF OffsetX= 0
DXF OffsetY= 0
DXF ScaleX= 0
DXF ScaleY= 0

--- MORRISFK.p01 (plan) ---

Plan Title=Floodplain
Program Version=4.10
Short Identifier=Floodplain
Geom File=g01
Flow File=f01
Subcritical Flow
K Sum by GR= 0
Std Step Tol= 0.01
Critical Tol= 0.01
Num of Std Step Trials= 20
Max Error Tol= 0.3
Flow Tol Ratio= 0.001
Split Flow NTrial= 30
Split Flow Tol= 0.02
Split Flow Ratio= 0.02
Log Output Level= 0
Friction Slope Method= 1
Unsteady Friction Slope Method= 2
Unsteady Bridges Friction Slope Method= 1
Parabolic Critical Depth
Global Vel Dist= 0 , 0 , 0
Global Log Level= 0
CheckData=True
Encroach Param=-1 ,0,0, 0
Run HTab= 0
Run UNet= 0
Run PostProcess= 0
Run WQNet= 0
UNET Theta= 0
UNET Theta Warmup= 0
UNET ZTol= 0
UNET ZSATol= 0
UNET MxIter= 0
UNET MaxInSteps= 0
UNET DtIC= 0
UNET DtMin= 0
UNET MaxCRTS= 0
UNET WFStab= 0
UNET SFStab= 0
UNET WFX= 1
UNET SFX= 1
UNET DSS MLevel= 1
UNET DZMax Abort= 0
UNET Convert EG Bridges= 0
UNET Use Existing IB Tables= 0
UNET Froude Reduction=False
UNET Froude Limit= 0
UNET Froude Power= 0
UNET Time Slicing=0,0, 5
UNET Junction Losses=0
DSS File=dss
Write IC File= 0
Write IC File at Sim End=0
Echo Input=False
Echo Parameters=False
Echo Output=False
Write Detailed= 0
WQ AD Non Conservative
WQ ULTIMATE=-1
WQ Max Comp Step=1HOUR
WQ Output Interval=15MIN
WQ Output Selected Increments= 0
WQ Output face flow=0
WQ Output face velocity=0
WQ Output face area=0
WQ Output face dispersion=0
WQ Output cell volume=0
WQ Output cell surface area=0
WQ Output cell continuity=0
WQ Output cumulative cell continuity=0
WQ Output face conc=0
WQ Output face dconc_dx=0
WQ Output face courant=0
WQ Output face peclet=0
WQ Output face adv mass=0
WQ Output face disp mass=0
WQ Output cell mass=0
WQ Output cell source sink temp=0
WQ Output cell source sink nsm=0
WQ Output MaxMinRange=-1
WQ Daily Max Min Mean=-1
WQ Daily Range=0
WQ Daily Time=0
WQ Create Restart=0
WQ Fixed Restart=0
WQ System Summary=0
WQ Use Fixed Temperature=0
Sorting and Armoring Iterations= 10
XS Update Threshold= 0.02
Hydraulics Update Threshold= 0.02
Energy Slope Method= 1
Volume Change Method= 0
XS Weighting Method= 0
Number of US Weighted Cross Sections= 1
Number of DS Weighted Cross Sections= 1
Upstream XS Weight=0.25
Main XS Weight=0.5
Downstream XS Weight=0.25
Number of DS XS's Weighted with US Boundary= 1
Upstream Boundary Weight= 1
Weight of XSs Associated with US Boundary= 0
Number of US XS's Weighted with DS Boundary= 1
Downstream Boundary Weight= 0.5
Weight of XSs Associated with DS Boundary= 0.5
Sediment Output Level= 4
Mass or Volume Output= 0
Output Increment Type= 1
Profile and TS Output Increment= 10
XS Output Flag= 0
XS Output Increment= 10
Disregard all LS=0
Disregard all Conn=0
Disregard all Breaches=0
Disregard all Pumps=0

--- MORRISFK.f01 (steady flow) ---

Flow Title=NFF Regression Equation
Program Version=4.10
Number of Profiles= 1
Profile Names=P100yr
River Rch & RM=MORRISFK,Main            ,29020.4
856.8197
River Rch & RM=MORRISFK,Main            ,28619.9
981.1514
River Rch & RM=MORRISFK,Main            ,25887.1
1073.429
River Rch & RM=MORRISFK,Main            ,25633.6
1335.094
River Rch & RM=MORRISFK,Main            ,23005.2
1418.798
River Rch & RM=MORRISFK,Main            ,19799
1565.497
River Rch & RM=MORRISFK,Main            ,18306.1
1706.502
River Rch & RM=MORRISFK,Main            ,16842.2
1809.165
River Rch & RM=MORRISFK,Main            ,12246.8
1970.085
River Rch & RM=MORRISFK,Main            ,11933.2
2537.294
River Rch & RM=MORRISFK,Main            ,10719.9
2651.715
River Rch & RM=MORRISFK,Main            ,4907.8
2861.494
River Rch & RM=MORRISFK,Main            ,563.6
3144.381
Boundary for River Rch & Prof#=MORRISFK,Main            , 1
Up Type= 0
Dn Type= 3
Dn Slope=0.0066
DSS Import GetInterval= 0
DSS Import GetPeak= 0
DSS Import FillOption= 0

--- MORRISFK.g01 (geometry) ---

Geom Title=USGS 10m DEM
Program Version=4.10

River Reach=MORRISFK        ,Main
Reach XY= 30
     1874710.097       473844.78     1874789.703      474262.783
     1874390.066       475012.64     1873053.298      475444.895
     1872621.791       476886.65     1871663.994      477547.448
     1871188.582      478722.036     1870722.818      478945.182
     1869918.431      480214.138     1869902.423      480508.842
     1870422.493      481093.909     1870005.409      481603.076
     1869884.336      482834.469     1868317.619      484547.351
     1867436.773      484439.149     1865898.512      484631.938
     1865510.878      485435.492     1865530.256      485910.363
     1865050.388      486262.106     1865116.426      487624.566
     1865983.296      488512.025     1866082.852      489162.237
     1866757.465      489206.296     1867380.729      489514.976
     1867264.962      489858.273     1866643.135      490487.138
     1867379.759      491086.307     1867282.361      492003.528
     1867866.465      493735.407     1868059.602       493844.33

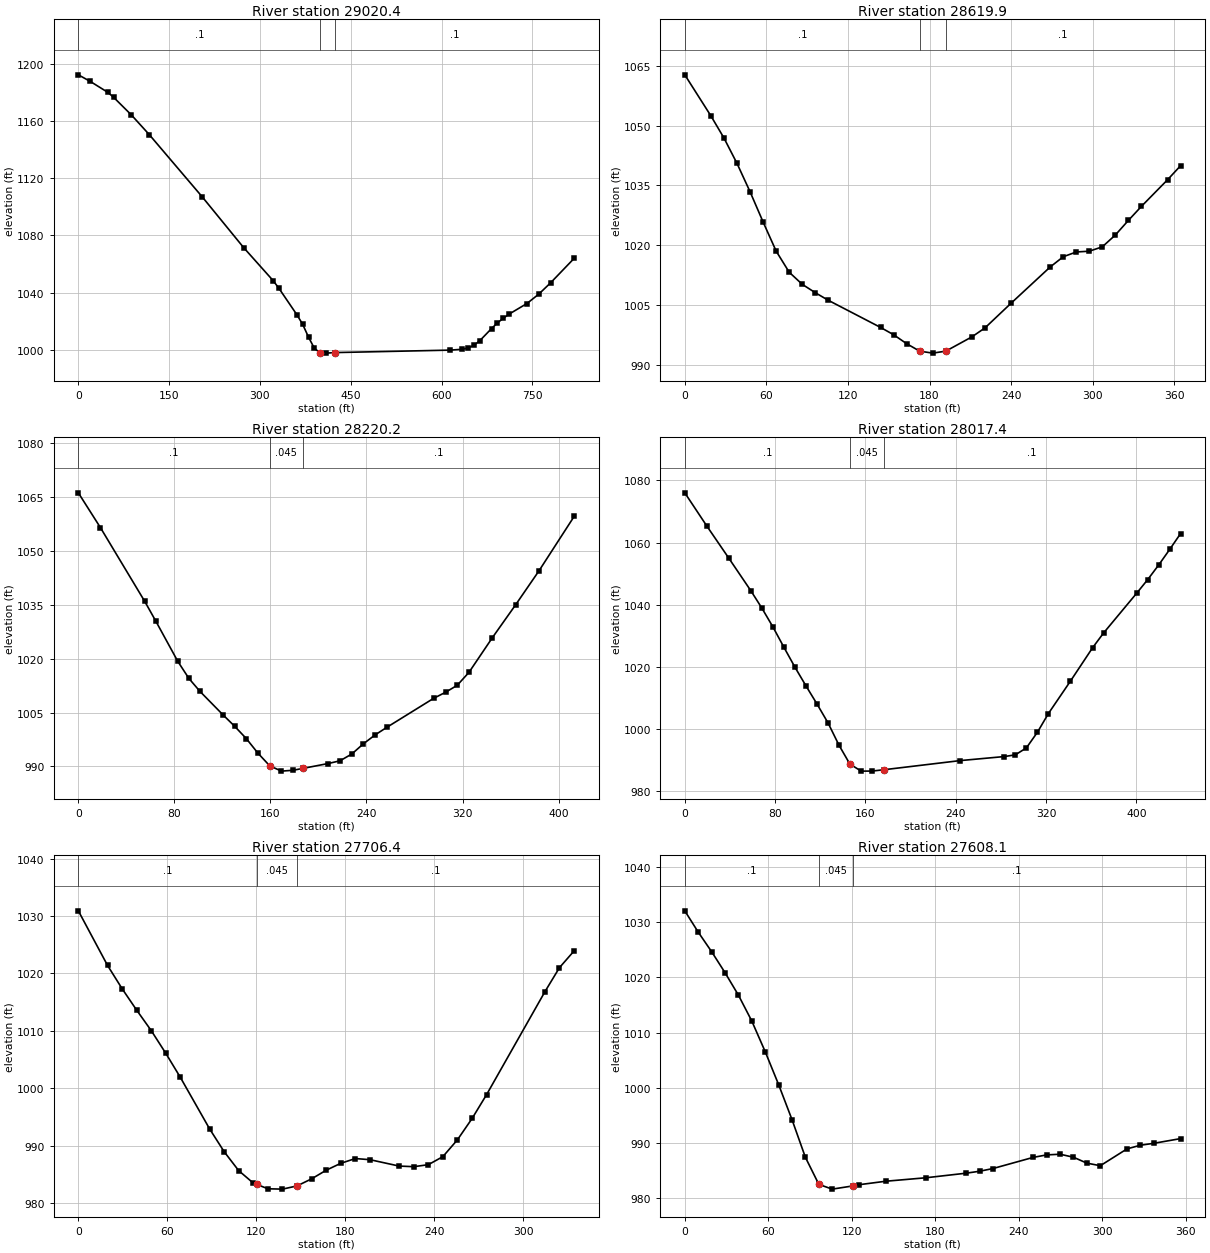
Type RM Length L Ch R = 1 ,29020.4 ,396.3,400.5,404.2
XS GIS Cut Line= 3
     1874303.264      473892.493     1874711.019      473854.738
     1875118.775      473816.982
#Sta/Elev= 30
       0 1192.59    19.5 1188.02    48.8 1180.28    58.5 1176.74    87.8 1164.39
     117 1150.76   204.8 1106.97     273 1071.51   321.8 1048.32   331.5 1042.84
   360.8 1024.55   370.5 1017.77   380.2 1008.74     390 1000.78   399.8  997.66
   409.5  997.51   424.5   997.9   614.2  999.62   633.8 1000.19   643.5 1001.06
   653.2 1002.93     663 1006.16   682.5 1014.73   692.2 1018.66     702 1021.98
   711.8 1024.93     741 1032.29   760.5 1038.85     780 1046.75     819 1063.95
#Mann= 3 , 0 , 0
       0      .1       0   399.8    .045       0   424.5      .1       0
Bank Sta=399.8,424.5
XS Rating Curve= 0 ,0
Exp/Cntr=0.3,0.1

Type RM Length L Ch R = 1 ,28619.9 ,389.8,399.7,408.7
XS GIS Cut Line= 2
     1874611.042      474233.288     1874975.625      474243.705
#Sta/Elev= 30
       0  1062.7    19.2 1052.41    28.8 1046.87    38.4  1040.5      48  1033.4
    57.6 1025.82    67.2 1018.52    76.8 1013.23    86.4  1010.2      96  1008.1
   105.6 1006.19     144   999.4   153.6  997.57   163.2  995.32   172.8  993.45
   182.4  992.96     192  993.46   211.2  997.04   220.8  999.28     240 1005.47
   268.8 1014.56   278.4 1017.12     288 1018.31   297.5  1018.5   307.1  1019.6
   316.7 1022.56   326.3 1026.23   335.9 1029.75   355.1 1036.41   364.7 1039.94
#Mann= 3 , 0 , 0
       0      .1       0   172.8    .045       0     192      .1       0
Bank Sta=172.8,192
XS Rating Curve= 0 ,0
Exp/Cntr=0.3,0.1

Type RM Length L Ch R = 1 ,28220.2 ,191.4,202.7,214
XS GIS Cut Line= 4
     1874521.805       474526.17     1874613.472      474587.976
     1874789.167      474647.698     1874870.417      474731.726
#Sta/Elev= 29
       0 1066.16    18.4 1056.48    55.3 1035.95    64.5 1030.47    82.9 1019.22
    92.1  1014.5   101.3  1010.9   120.3 1004.43   130.1 1001.22   139.9  997.76
   149.6   993.7   159.4  990.18   169.2   988.7   178.9  988.94   186.9  989.45
   208.2  990.82     218  991.58   227.8  993.47   237.5  996.32   247.3   998.8
   257.1 1000.92   296.1 1008.99   305.9 1010.65   315.6 1012.59   325.4  1016.2
   344.8 1025.81   364.3 1035.02   383.8  1044.5     413  1059.6
#Mann= 3 , 0 , 0
       0      .1       0   159.4    .045       0   186.9      .1       0
Bank Sta=159.4,186.9
XS Rating Curve= 0 ,0
Exp/Cntr=0.3,0.1

Type RM Length L Ch R = 1 ,28017.4 ,310.1,311,311.2
XS GIS Cut Line= 2
     1874406.449      474645.642     1874742.717      474928.227
#Sta/Elev= 30
       0 1076.01    19.5 1065.33      39 1054.98    58.6 1044.46    68.3  1038.9
    78.1 1032.84    87.8 1026.32    97.6 1019.89   107.4 1013.86   117.1 1008.07
   126.9 1001.97   136.6   994.8   146.2  988.76   156.2  986.47   165.9  986.49
   176.2  986.91     244  989.86   283.1  991.16   292.8  991.71   302.6  993.95
   312.4  999.01   322.1 1005.01   341.6 1015.43   361.2 1026.16   370.9 1030.89
   400.2 1043.68     410 1048.08   419.7 1052.76   429.5 1057.79   439.2 1062.92
#Mann= 3 , 0 , 0
       0      .1       0   146.2    .045       0   176.2      .1       0
Bank Sta=146.2,176.2
XS Rating Curve= 0 ,0
Exp/Cntr=0.3,0.1

Type RM Length L Ch R = 1 ,27706.4 ,77.1,98.3,118.6
XS GIS Cut Line= 2
     1874284.102      474927.619     1874537.922      475144.981
#Sta/Elev= 30
       0  1030.9    19.7 1021.38    29.5 1017.33    39.3  1013.6    49.1 1010.04
      59 1006.05    68.8 1001.86    88.5  992.89    98.3  988.92   108.1  985.62
   117.9  983.46   120.3  983.22   127.8  982.46   137.6   982.4   147.4  982.96
   157.3   984.2   167.1   985.7   176.9   986.9   186.7  987.73   196.6  987.53
   216.2  986.42   226.1  986.31   235.9  986.66   245.7  988.06   255.5  990.99
   265.4  994.71   275.2  998.88   314.5 1016.81   324.3    1021   334.2 1023.93
#Mann= 3 , 0 , 0
       0      .1       0   120.3    .045       0   147.4      .1       0
Bank Sta=120.3,147.4
XS Rating Curve= 0 ,0
Exp/Cntr=0.3,0.1

Type RM Length L Ch R = 1 ,27608.1 ,131.2,107.6,84
XS GIS Cut Line= 2
     1874273.339      474932.714     1874339.659      475282.714
#Sta/Elev= 29
       0 1032.04     9.6  1028.2    19.3 1024.63    28.9 1020.84    38.5 1016.78
    48.1  1012.1    57.8 1006.51    67.4 1000.57      77  994.24    86.6  987.42
    96.3   982.5   105.9  981.64   120.5  982.21   125.2  982.44   144.4  983.07
   173.3   983.7   202.2  984.53   211.8  984.88   221.4  985.37   250.3  987.39
     260  987.84   269.6  987.96   279.2  987.42   288.8  986.35   298.5  985.88
   317.7  988.93   327.3  989.59     337  989.94   356.2  990.79
#Mann= 3 , 0 , 0
       0      .1       0    96.3    .045       0   120.5      .1       0
Bank Sta=96.3,120.5
XS Rating Curve= 0 ,0
Exp/Cntr=0.3,0.1

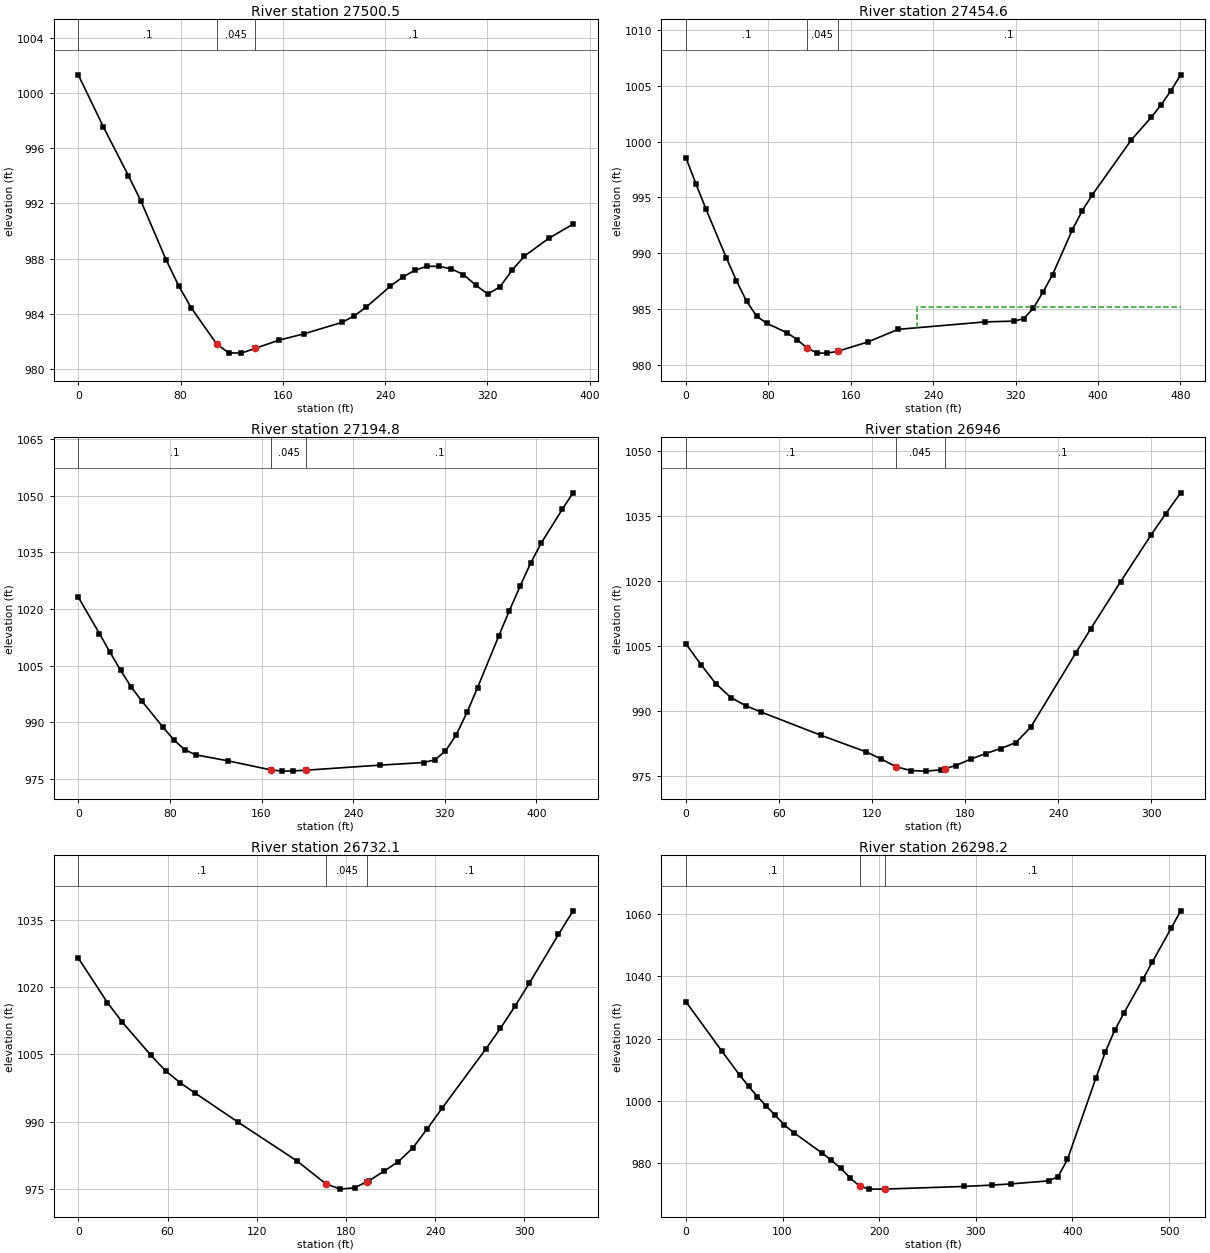
Type RM Length L Ch R = 1 ,27500.5 ,45.5,46,45.5
XS GIS Cut Line= 3
     1874093.981      475006.971     1874263.425      475124.193
     1874336.534      475289.658
#Sta/Elev= 30
       0  1001.3    19.6  997.53    39.2     994    49.1  992.14    68.7   987.9
    78.5  986.03    88.3  984.43   108.4  981.79   117.7  981.17   127.6  981.15
   138.4   981.5     157  982.09   176.6  982.55     206  983.37   215.6  983.83
   225.1  984.48   244.1     986   253.6  986.65   263.2  987.15   272.7  987.44
   282.2  987.43   291.7  987.25   301.2  986.84   310.8  986.07   320.3  985.43
   329.8  985.95   339.3  987.16   348.8  988.17   367.9  989.46   386.9  990.49
#Mann= 3 , 0 , 0
       0      .1       0   108.4    .045       0   138.4      .1       0
Bank Sta=108.4,138.4
XS Rating Curve= 0 ,0
Exp/Cntr=0.3,0.1

Type RM Length L Ch R = 1 ,27454.6 ,237.7,259.8,282.3
XS GIS Cut Line= 4
     1874052.245      475031.485     1874221.689      475148.707
     1874286.808      475283.698     1874293.982      475407.898
#Sta/Elev= 30
       0  998.56     9.8  996.18    19.6  993.92    39.2  989.58    49.1  987.51
    58.9  985.68    68.7  984.34    78.5   983.7    98.1  982.86   107.9  982.25
   117.7  981.48   127.6  981.03   137.4  981.03   147.2  981.19   176.6  982.03
     206  983.16   290.4  983.83   318.4   983.9   327.8  984.11   337.2  985.04
   346.6   986.5   355.9  988.06   375.1  992.08   384.6  993.77   394.2  995.18
   432.5 1000.16   451.6 1002.16   461.2 1003.28   470.8 1004.55   480.3 1005.98
#Mann= 3 , 0 , 0
       0      .1       0   117.7    .045       0   147.2      .1       0
#XS Ineff= 2 , 0
                           223.9          985.18
Permanent Ineff=
       F       F
Bank Sta=117.7,147.2
XS Rating Curve= 0 ,0
Exp/Cntr=0.3,0.1

Type RM Length L Ch R = 1 ,27194.8 ,251.6,248.8,245.8
XS GIS Cut Line= 4
      1873889.99      475023.538     1873897.313      475097.143
     1873955.708      475346.538      1873964.99      475447.982
#Sta/Elev= 29
       0 1023.12    18.5 1013.47    27.7 1008.52      37 1003.76    46.2  999.34
    55.5  995.63      74  988.69    83.5  985.36    92.9  982.74   102.4  981.42
   130.9   979.8   168.5  977.39   178.3  977.09   187.8  977.15   198.5  977.33
   263.7  978.68   301.6  979.36   311.1  980.06   320.6  982.39   330.1  986.76
   339.4  992.61   348.6  999.17   367.2 1012.88   376.4 1019.55   385.7 1025.95
   394.9 1032.09   404.2 1037.41   422.7 1046.39     432 1050.71
#Mann= 3 , 0 , 0
       0      .1       0   168.5    .045       0   198.5      .1       0
Bank Sta=168.5,198.5
XS Rating Curve= 0 ,0
Exp/Cntr=0.3,0.1

Type RM Length L Ch R = 1 ,26946   ,214.9,213.9,212.9
XS GIS Cut Line= 2
     1873640.646      475143.465     1873743.146      475445.548
#Sta/Elev= 26
       0 1005.47     9.7 1000.68    19.3  996.28      29  993.08    38.7  991.18
    48.3  989.77      87  984.38     116  980.57   125.7  978.95   135.3  977.13
     145  976.23   154.7   976.1   164.3  976.39   167.1  976.68     174  977.39
   183.7  978.88   193.3  980.16     203  981.32   212.7  982.68   222.3  986.23
   251.3 1003.33     261 1008.95   280.3 1019.84   299.7  1030.5   309.3 1035.48
     319 1040.33
#Mann= 3 , 0 , 0
       0      .1       0   135.3    .045       0   167.1      .1       0
Bank Sta=135.3,167.1
XS Rating Curve= 0 ,0
Exp/Cntr=0.3,0.1

Type RM Length L Ch R = 1 ,26732.1 ,440.2,433.9,426.4
XS GIS Cut Line= 2
     1873428.732      475195.727     1873544.986      475507.462
#Sta/Elev= 25
       0 1026.44    19.6 1016.51    29.4 1012.24    48.9 1004.75    58.7 1001.34
    68.5  998.66    78.3  996.43   107.6  989.86   146.8  981.32   166.4  976.19
   176.1  974.98   185.9   975.3   194.4  976.67   195.7  976.88   205.5  978.96
   215.3  981.11   225.1  984.22   234.8  988.48   244.6  992.98     274 1006.16
   283.8 1010.75   293.6 1015.67   303.4 1020.88   322.9 1031.69   332.7 1036.95
#Mann= 3 , 0 , 0
       0      .1       0   166.4    .045       0   194.4      .1       0
Bank Sta=166.4,194.4
XS Rating Curve= 0 ,0
Exp/Cntr=0.3,0.1

Type RM Length L Ch R = 1 ,26298.2 ,428.6,411.1,392.5
XS GIS Cut Line= 3
     1873032.859      475249.967     1873039.803      475351.529
     1873266.366      475693.543
#Sta/Elev= 30
       0 1031.83      37 1016.05    55.5 1008.29    64.8 1004.69      74 1001.36
    83.3  998.23    92.6   995.3   101.8  992.22   111.6  989.75   140.9   983.2
   150.6  980.86   160.4  978.25   170.2  975.12   179.9  972.53   189.7   971.6
   206.4  971.62   287.4  972.46   316.7  972.89   336.2  973.28   375.3  974.25
   385.1  975.61   394.8  981.13   424.1 1007.16   433.9 1015.58   443.7 1022.63
   453.4 1028.26     473 1039.12   482.7 1044.63   502.3 1055.54     512 1061.05
#Mann= 3 , 0 , 0
       0      .1       0   179.9    .045       0   206.4      .1       0
Bank Sta=179.9,206.4
XS Rating Curve= 0 ,0
Exp/Cntr=0.3,0.1

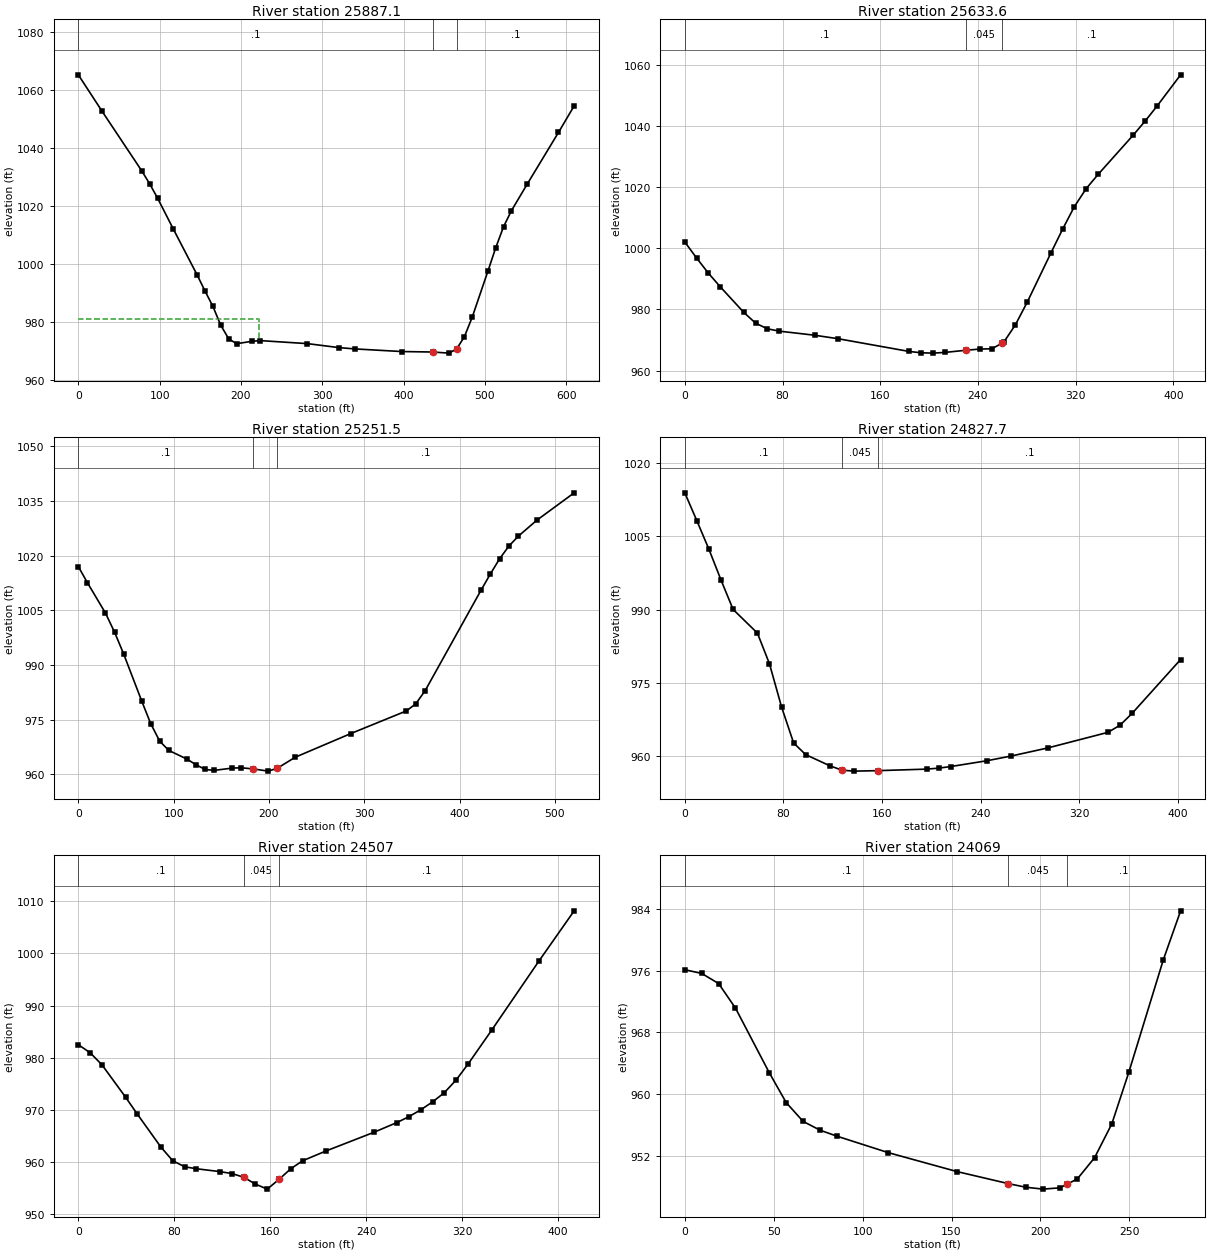
Type RM Length L Ch R = 1 ,25887.1 ,263.6,253.5,243.2
XS GIS Cut Line= 3
     1872571.921      475733.474     1872802.824      475697.883
     1873149.178      475844.585
#Sta/Elev= 30
       0 1065.23    29.2 1052.65    77.9 1032.12    87.6 1027.66    97.4 1022.69
   116.8    1012     146  996.21   155.8  990.59   165.5  985.29   175.2  978.76
     185  974.06   194.7  972.41   214.2  973.26   223.9  973.47   281.8  972.43
   320.4  971.06   339.7  970.61   397.6   969.7   436.2  969.53   455.5  969.15
   465.1  970.51   474.8  974.82   484.4  981.54   503.7  997.43   513.3 1005.49
     523 1012.82   532.6  1018.3   551.9 1027.43   590.5 1045.34   609.8 1054.51
#Mann= 3 , 0 , 0
       0      .1       0   436.2    .045       0   465.1      .1       0
#XS Ineff= 2 , 0
          221.79  980.88
Permanent Ineff=
       F       F
Bank Sta=436.2,465.1
XS Rating Curve= 0 ,0
Exp/Cntr=0.3,0.1

Type RM Length L Ch R = 1 ,25633.6 ,375.2,382,389.1
XS GIS Cut Line= 2
      1872696.26       476010.51     1873101.401      476035.777
#Sta/Elev= 30
       0  1002.1     9.7  996.82    19.3  991.89      29  987.43    48.3  979.04
      58   975.5    67.6  973.67    77.3   972.9   106.3  971.56   125.6  970.41
   183.6  966.25   193.3  965.82     203   965.7   212.6  965.92   229.9  966.63
   241.6  967.04   251.3  967.12   259.9  968.98     261  969.22   270.6  974.94
   280.3  982.38   299.6   998.4   309.3  1006.3   318.9 1013.66   328.6 1019.57
   338.3  1024.2   367.3 1037.18   376.9 1041.71   386.6  1046.6   405.9 1056.83
#Mann= 3 , 0 , 0
       0      .1       0   229.9    .045       0   259.9      .1       0
Bank Sta=229.9,259.9
XS Rating Curve= 0 ,0
Exp/Cntr=0.3,0.1

Type RM Length L Ch R = 1 ,25251.5 ,413,423.8,433.5
XS GIS Cut Line= 3
     1872668.761      476329.324     1872912.095      476409.741
     1873175.636      476396.083
#Sta/Elev= 30
       0 1016.98     9.5 1012.57    28.5 1004.22      38     999    47.5  993.06
    66.4  980.18    75.9  973.94    85.4   969.1    94.9  966.58   113.9  964.21
   123.4  962.66   132.9  961.37   142.4   961.1   161.4  961.73   170.8  961.82
     183  961.52   199.3   960.9   208.8   961.7   227.8  964.74   285.6  971.17
   344.2  977.41     354  979.35   363.8  982.93   422.4 1010.46   432.2 1014.92
     442 1019.13   451.8 1022.62   461.5 1025.29   481.1  1029.7   520.2  1037.2
#Mann= 3 , 0 , 0
       0      .1       0     183    .045       0   208.8      .1       0
Bank Sta=183,208.8
XS Rating Curve= 0 ,0
Exp/Cntr=0.3,0.1

Type RM Length L Ch R = 1 ,24827.7 ,305,320.7,335.8
XS GIS Cut Line= 2
     1872516.539      476629.403      1872842.65      476864.958
#Sta/Elev= 24
       0 1013.87     9.8 1008.16    19.6 1002.32    29.4  996.04    39.2  990.04
    58.9  985.21    68.7  978.93    78.5  970.12    88.3  962.75    98.1  960.37
   117.7  958.09   127.6  957.19   137.4     957     157   957.1   196.2  957.41
     206  957.61   215.9  957.94   245.3  959.13   264.9  960.09   294.4  961.73
   343.4  964.93   353.2   966.4     363  968.82   402.3  979.81
#Mann= 3 , 0 , 0
       0      .1       0   127.6    .045       0     157      .1       0
Bank Sta=127.6,157
XS Rating Curve= 0 ,0
Exp/Cntr=0.3,0.1

Type RM Length L Ch R = 1 ,24507   ,436.9,438.1,438.7
XS GIS Cut Line= 2
     1872442.443      476815.825     1872612.582      477192.561
#Sta/Elev= 29
       0   982.5     9.8  980.96    19.7  978.64    39.4  972.43    49.2  969.17
    68.9  962.84    78.7  960.24    88.6  959.08    98.4   958.7   118.1  958.15
     128  957.78   137.8  957.08   147.6  955.76   157.5  954.79   167.3  956.66
   177.2  958.71     187  960.23   206.7  962.13   246.1  965.66   265.7  967.57
   275.6  968.69   285.4  969.99   295.3  971.52   305.1  973.28     315  975.73
   324.8  978.74   344.5  985.24   383.8  998.47   413.4 1008.18
#Mann= 3 , 0 , 0
       0      .1       0   137.8    .045       0   167.3      .1       0
Bank Sta=137.8,167.3
XS Rating Curve= 0 ,0
Exp/Cntr=0.3,0.1

Type RM Length L Ch R = 1 ,24069   ,229.5,224.2,218.4
XS GIS Cut Line= 3
     1872097.488       476999.82     1872126.751      477090.146
      1872197.82      477259.655
#Sta/Elev= 22
       0  976.14     9.5  975.66      19  974.35    28.5  971.16    47.5  962.78
      57  958.91    66.5  956.47      76  955.33    85.4  954.56   114.3  952.42
     153  949.96     182  948.39   191.7  947.93   201.4  947.68     211  947.85
   214.8   948.3   220.7     949   230.4  951.75   240.1  956.14   249.7  962.86
   269.1  977.45   278.8  983.78
#Mann= 3 , 0 , 0
       0      .1       0     182    .045       0   214.8      .1       0
Bank Sta=182,214.8
XS Rating Curve= 0 ,0
Exp/Cntr=0.3,0.1

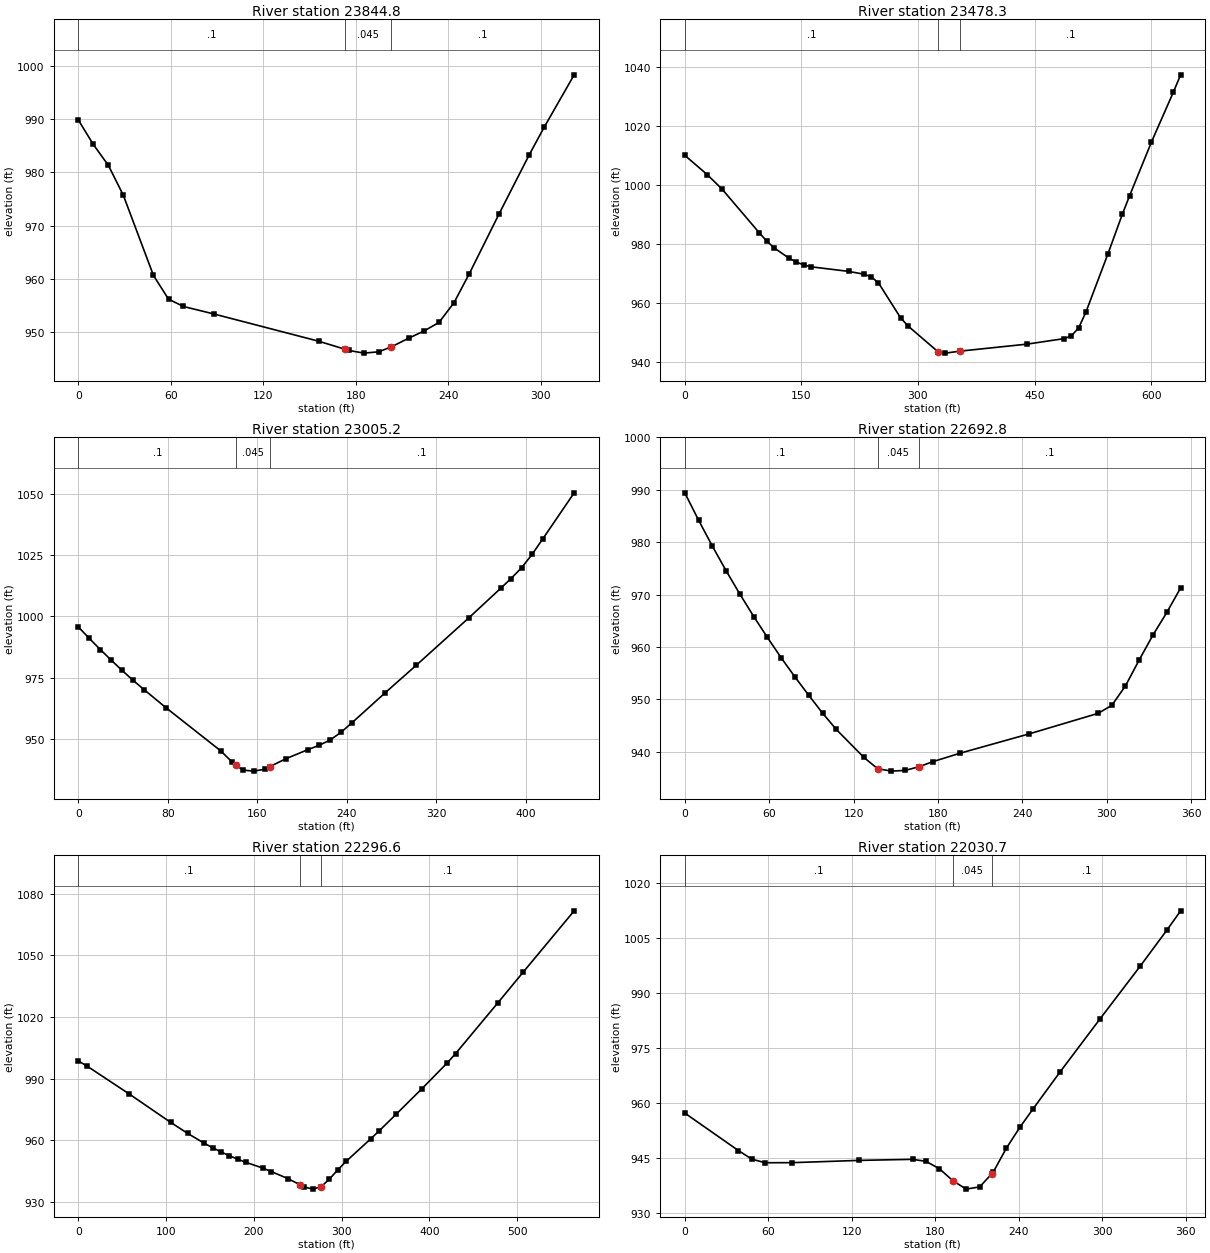
Type RM Length L Ch R = 1 ,23844.8 ,370.3,366.5,361.7
XS GIS Cut Line= 2
     1871851.934      477098.312     1872028.266      477367.227
#Sta/Elev= 23
       0  989.87     9.7  985.27    19.5  981.32    29.2   975.7    48.7  960.65
    58.5  956.17    68.2  954.79    87.7   953.4   155.9  948.26   173.1  946.74
   175.4  946.53   185.2  946.02   194.9  946.27   203.1  947.21   214.4  948.85
   224.1  950.16   233.9  951.79   243.6  955.47   253.4  960.85   272.8  972.15
   292.3  983.23   302.1  988.48   321.6  998.36
#Mann= 3 , 0 , 0
       0      .1       0   173.1    .045       0   203.1      .1       0
Bank Sta=173.1,203.1
XS Rating Curve= 0 ,0
Exp/Cntr=0.3,0.1

Type RM Length L Ch R = 1 ,23478.3 ,489.1,473.1,455.7
XS GIS Cut Line= 4
     1871442.918      477306.589     1871645.105      477435.026
     1871797.883      477606.693     1871956.772       477663.36
#Sta/Elev= 30
       0 1010.06    28.7 1003.58    47.9  998.65    95.8  983.87   105.4  981.08
     115  978.74   134.1  975.28   143.7  973.93   153.3  972.96   162.9  972.34
   210.8   970.8     230  969.88   239.5  969.03   249.1  966.96   277.8  955.04
   287.4   952.3   325.7  943.64   335.3  943.15   354.4  943.83   440.6   946.2
   488.1  948.06   497.4  948.98   506.8  951.68   516.2  957.08   544.3  976.62
   563.1  990.21   572.4  996.44   600.5 1014.59   628.7 1031.47     638  1037.3
#Mann= 3 , 0 , 0
       0      .1       0   325.7    .045       0   354.4      .1       0
Bank Sta=325.7,354.4
XS Rating Curve= 0 ,0
Exp/Cntr=0.3,0.1

Type RM Length L Ch R = 1 ,23005.2 ,299.5,312.4,325.1
XS GIS Cut Line= 3
     1871443.258      477874.596     1871705.671      477953.428
     1871864.439       478011.61
#Sta/Elev= 30
       0   995.7     9.8  991.02    19.6  986.46    29.4  982.11    39.1  977.92
    48.9  973.87    58.7  970.07    78.3  962.67   127.2  945.03     137  940.62
   141.2  939.14   146.8  937.16   156.6  936.72   166.4  937.47   171.2  938.59
   185.9  941.88   205.5  945.56   215.3   947.3   225.1  949.47   234.9  952.65
   244.6  956.52     274  968.68   302.2  980.11   349.2  999.51   377.3 1011.44
   386.7 1015.51   396.1 1019.89   405.5  1025.4   414.9 1031.61   443.1 1050.56
#Mann= 3 , 0 , 0
       0      .1       0   141.2    .045       0   171.2      .1       0
Bank Sta=141.2,171.2
XS Rating Curve= 0 ,0
Exp/Cntr=0.3,0.1

Type RM Length L Ch R = 1 ,22692.8 ,409.7,396.2,382.9
XS GIS Cut Line= 2
     1871313.814      478076.471     1871579.439      478308.068
#Sta/Elev= 27
       0   989.4     9.8  984.18    19.6  979.23    29.4  974.53    39.2  970.06
      49  965.82    58.7  961.83    68.5  957.95    78.3  954.29    88.1   950.8
    97.9   947.4   107.7  944.28   127.3  938.95     137  936.81   146.8  936.34
   156.6  936.48   166.4  937.17   176.2  938.14   195.8  939.77   244.7  943.44
   293.7  947.35   303.5  948.88   313.2   952.6     323  957.56   332.8  962.32
   342.6   966.6   352.4  971.27
#Mann= 3 , 0 , 0
       0      .1       0     137    .045       0   166.4      .1       0
Bank Sta=137,166.4
XS Rating Curve= 0 ,0
Exp/Cntr=0.3,0.1

Type RM Length L Ch R = 1 ,22296.6 ,249.3,265.9,281.7
XS GIS Cut Line= 4
     1870985.793      478379.249     1871144.682      478485.915
     1871290.793      478526.471     1871479.682      478643.138
#Sta/Elev= 30
       0  998.67     9.6  996.26    57.4  982.76   105.2  968.77   124.4  963.46
   143.5  958.59   153.1  956.41   162.7  954.36   172.2  952.54   181.8   950.8
   191.4  949.26   210.3   946.5   219.8  944.85   238.8  941.41   252.1  938.52
   257.7  937.31   267.2  936.28   276.7  937.49   286.1  941.13   295.6  945.67
   305.1  949.77   333.5  960.89     343  964.72   362.3   972.8   391.3  985.06
   420.2  997.64   429.9 1002.26   478.2 1027.04   507.1 1041.99     565 1071.74
#Mann= 3 , 0 , 0
       0      .1       0   252.1    .045       0   276.7      .1       0
Bank Sta=252.1,276.7
XS Rating Curve= 0 ,0
Exp/Cntr=0.3,0.1

Type RM Length L Ch R = 1 ,22030.7 ,499.6,497.4,494.7
XS GIS Cut Line= 2
     1871017.306      478611.744     1871264.307      478868.545
#Sta/Elev= 22
       0   957.3    38.5  947.08    48.2  944.72    57.8  943.75      77  943.77
   125.2  944.39   163.7  944.68   173.3  944.13     183  942.11   192.6  938.85
   202.2  936.55   211.9  937.17   220.7  940.77   221.5   941.1   231.1  947.74
   240.8  953.43   250.4  958.52   269.6  968.49   298.5  983.06   327.4  997.47
   346.7 1007.36   356.3 1012.49
#Mann= 3 , 0 , 0
       0      .1       0   192.6    .045       0   220.7      .1       0
Bank Sta=192.6,220.7
XS Rating Curve= 0 ,0
Exp/Cntr=0.3,0.1

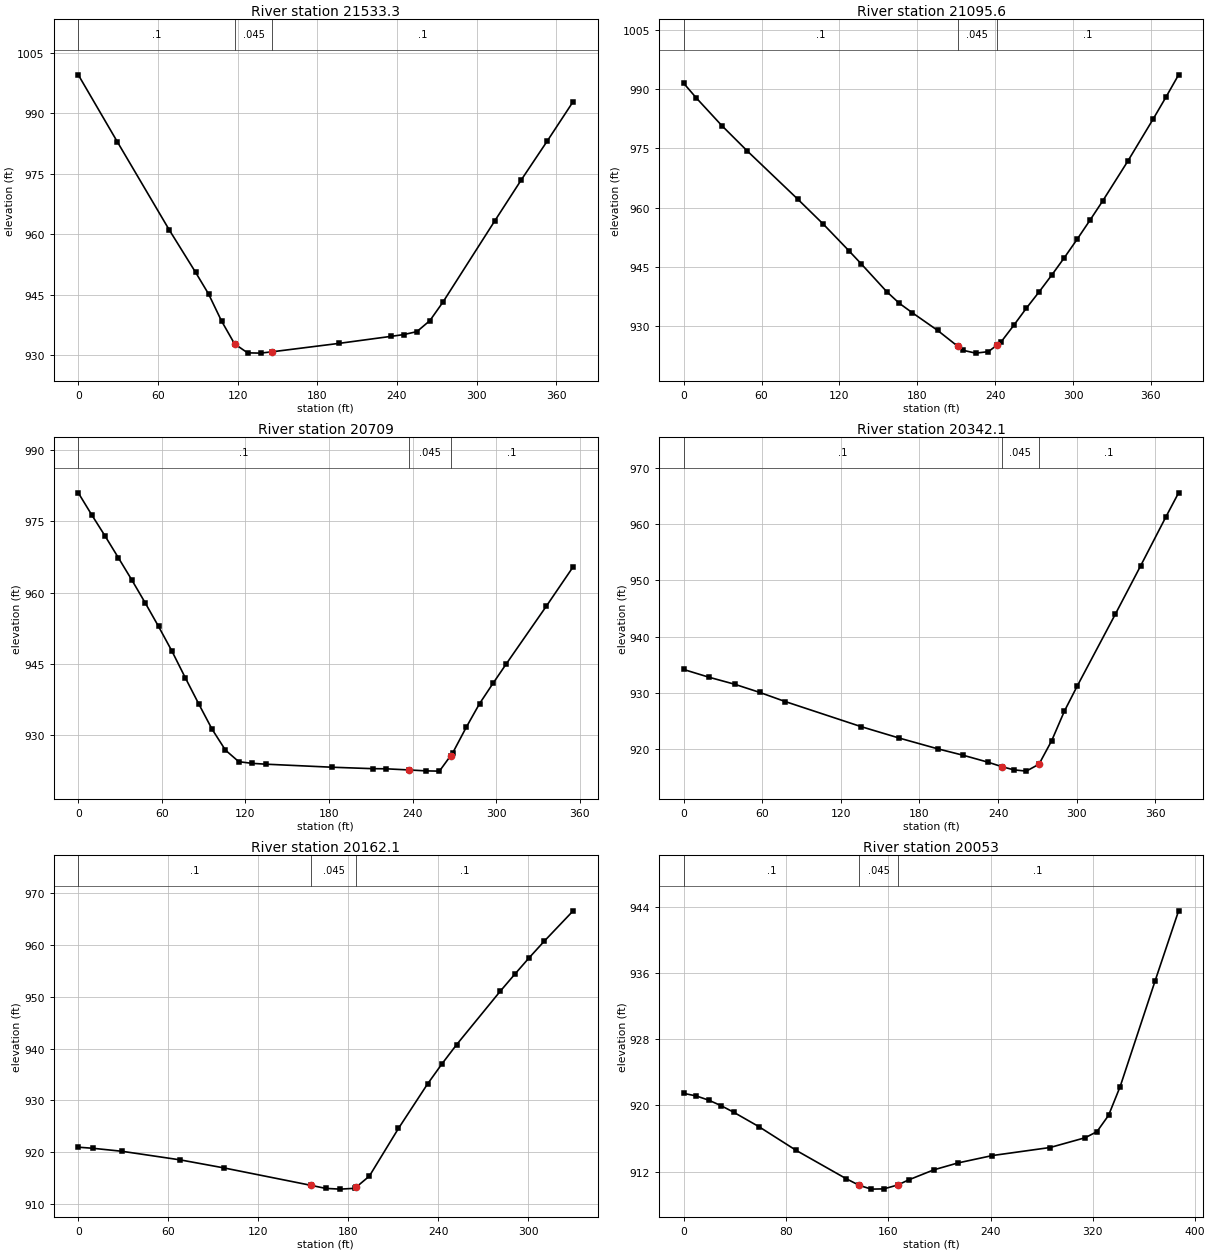
Type RM Length L Ch R = 1 ,21533.3 ,439.5,437.7,434.7
XS GIS Cut Line= 2
     1870614.904       478870.04     1870894.418      479116.568
#Sta/Elev= 20
       0  999.47    29.4  982.87    68.6  960.98    88.3  950.54    98.1  945.16
   107.9  938.44   117.7  932.78   127.5  930.56   137.3  930.49   146.2  930.83
   196.2   932.9   235.4  934.64   245.2  935.09     255  935.82   264.8  938.55
   274.6  943.12   313.8  963.34   333.5  973.37   353.1  983.02   372.7  992.84
#Mann= 3 , 0 , 0
       0      .1       0   117.7    .045       0   146.2      .1       0
Bank Sta=117.7,146.2
XS Rating Curve= 0 ,0
Exp/Cntr=0.3,0.1

Type RM Length L Ch R = 1 ,21095.6 ,384.2,386.6,389.2
XS GIS Cut Line= 2
     1870377.755      479221.174     1870683.758      479448.733
#Sta/Elev= 30
       0  991.49     9.8  987.75    29.3   980.8    48.9  974.38      88  962.11
   107.6  955.81   127.1  949.15   136.9  945.72   156.4  938.73   166.2  935.76
     176  933.42   195.6  928.92   211.3  924.85   215.1  923.89   224.9  923.16
   234.7  923.53   241.3  925.17   244.4  925.94   254.2  930.16     264  934.54
   273.8  938.66   283.6  942.94   293.3  947.35   303.1  951.98   312.9  956.76
   322.7  961.64   342.2   971.8   361.8   982.5   371.6  988.02   381.3  993.64
#Mann= 3 , 0 , 0
       0      .1       0   211.3    .045       0   241.3      .1       0
Bank Sta=211.3,241.3
XS Rating Curve= 0 ,0
Exp/Cntr=0.3,0.1

Type RM Length L Ch R = 1 ,20709   ,367.6,366.9,366.2
XS GIS Cut Line= 2
      1870160.17      479511.766     1870425.242      479748.182
#Sta/Elev= 29
       0  981.04     9.6  976.41    19.2  971.94    28.8  967.32    38.4  962.66
      48  957.83    57.6  952.84    67.2  947.64    76.8  942.01    86.4  936.52
      96  931.16   105.6  926.74   115.2  924.29   124.8  923.94   134.4  923.77
   182.4  923.12   211.2  922.82   220.8  922.79   237.3  922.55   249.6  922.35
   259.2   922.3   267.3  925.57   268.8  926.18   278.4  931.52     288  936.54
   297.6   940.8   307.2  944.94     336  957.14   355.2  965.43
#Mann= 3 , 0 , 0
       0      .1       0   237.3    .045       0   267.3      .1       0
Bank Sta=237.3,267.3
XS Rating Curve= 0 ,0
Exp/Cntr=0.3,0.1

Type RM Length L Ch R = 1 ,20342.1 ,180.3,180,179.6
XS GIS Cut Line= 2
     1869916.273      479793.476      1870204.05      480038.476
#Sta/Elev= 21
       0  934.15    19.4  932.77    38.8  931.54    58.2  930.07    77.5  928.46
   135.7  923.99   164.7  921.97   193.8  920.08   213.2  918.94   232.6  917.68
   242.7  916.92     252  916.34   261.6  916.11   271.3  917.34     281  921.52
   290.7  926.76   300.4  931.17   329.5  943.93   348.9  952.55   368.2  961.24
   377.9  965.51
#Mann= 3 , 0 , 0
       0      .1       0   242.7    .045       0   271.3      .1       0
Bank Sta=242.7,271.3
XS Rating Curve= 0 ,0
Exp/Cntr=0.3,0.1

Type RM Length L Ch R = 1 ,20162.1 ,99.4,109.1,118.9
XS GIS Cut Line= 2
     1869863.687      479987.502     1870117.384      480198.476
#Sta/Elev= 20
       0  920.93     9.7  920.72    29.1  920.14    67.9  918.48      97  916.93
   155.4  913.54     165  912.96   174.7  912.82   184.4  912.98   185.4  913.22
   194.1  915.34   213.5  924.56   232.9  933.16   242.6  937.08   252.3  940.77
   281.4   951.1   291.1  954.39   300.8  957.61   310.6  960.73     330  966.64
#Mann= 3 , 0 , 0
       0      .1       0   155.4    .045       0   185.4      .1       0
Bank Sta=155.4,185.4
XS Rating Curve= 0 ,0
Exp/Cntr=0.3,0.1

Type RM Length L Ch R = 1 ,20053   ,55.1,56.1,57
XS GIS Cut Line= 4
     1869850.717      480060.143     1869963.778      480231.619
     1870006.532      480300.716     1870106.898      480303.823
#Sta/Elev= 23
       0  921.46     9.8  921.15    19.6  920.64    29.3  919.97    39.1  919.18
    58.7  917.45      88  914.57   127.2  911.14   137.4  910.34   146.7  909.89
   156.5  909.92   167.4  910.39     176  911.01   195.6  912.22   214.4  913.05
   241.5  913.95   286.6  914.92     314   916.1   323.2  916.83   332.3   918.8
   341.4  922.29   368.8  935.09   387.1  943.52
#Mann= 3 , 0 , 0
       0      .1       0   137.4    .045       0   167.4      .1       0
Bank Sta=137.4,167.4
XS Rating Curve= 0 ,0
Exp/Cntr=0.3,0.1

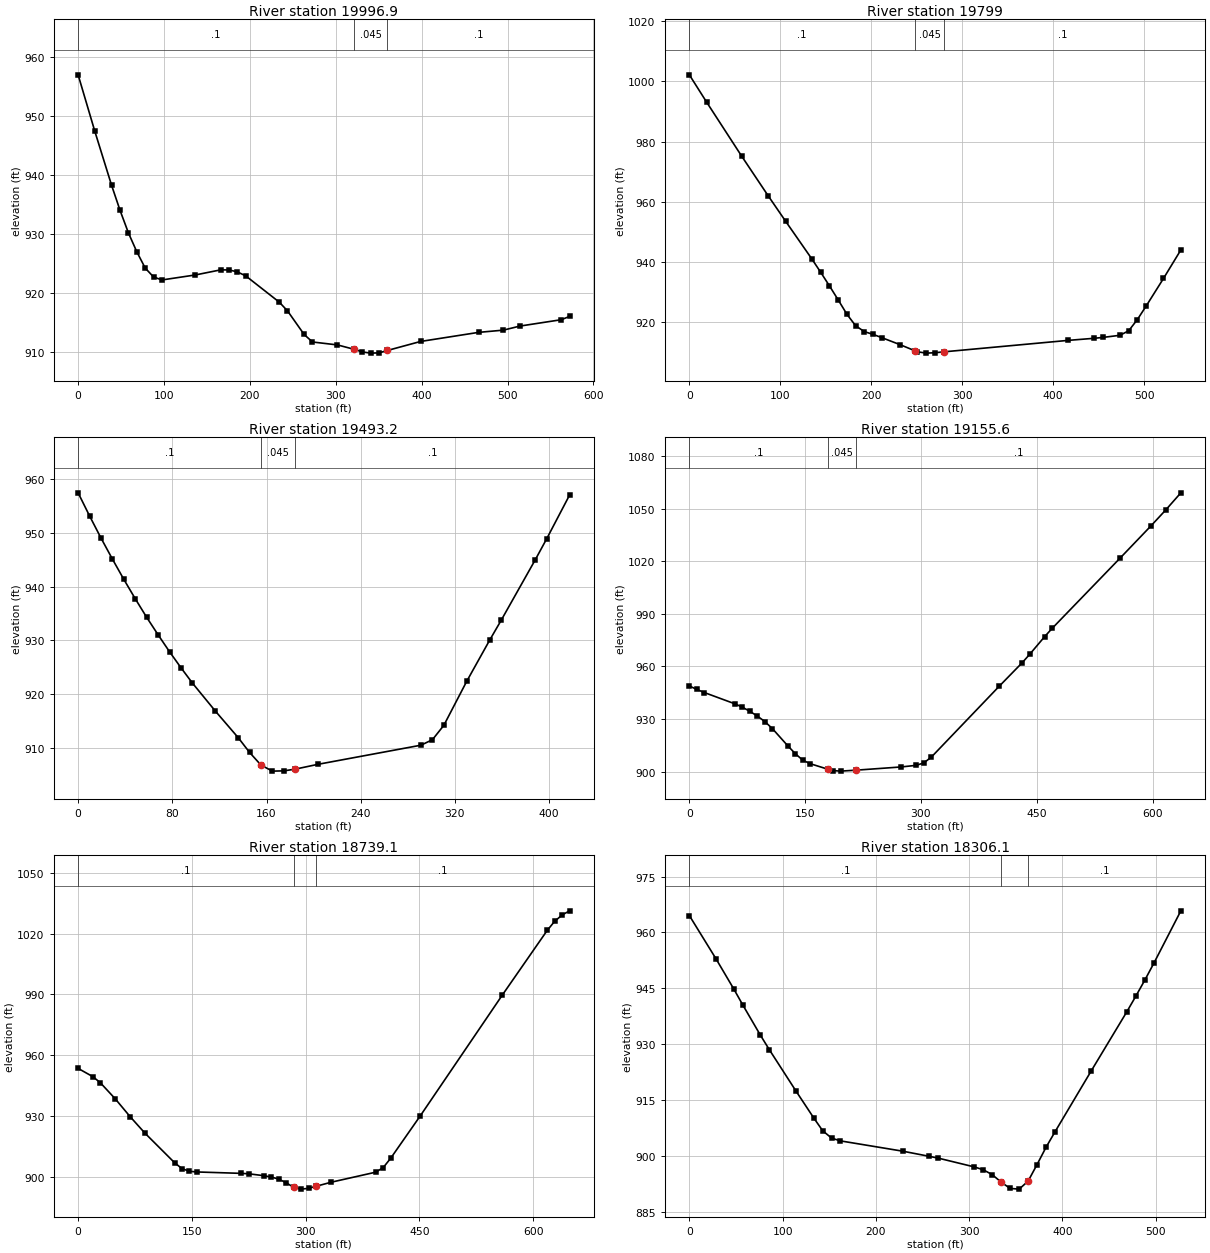
Type RM Length L Ch R = 1 ,19996.9 ,232.6,197.8,162.8
XS GIS Cut Line= 5
     1869687.106      479977.677     1869843.513      480138.693
     1869928.633      480268.246     1869988.801      480367.133
     1870065.835       480365.21
#Sta/Elev= 30
       0  957.04    19.5  947.44      39  938.29    48.8  934.06    58.6  930.22
    68.3  927.04    78.1  924.27    87.8  922.76    97.6  922.25   136.6   923.1
   165.9  923.96   175.7  923.95   185.4  923.62   195.2  922.94   234.2  918.49
   243.8  917.01   263.2     913   272.9  911.73     302  911.23   321.4  910.49
     331  910.04   340.7  909.84   350.4  909.88   360.1  910.29   398.8  911.82
   466.3  913.36   495.2  913.74   514.5  914.43   562.7  915.51   572.3  916.07
#Mann= 3 , 0 , 0
       0      .1       0   321.4    .045       0   360.1      .1       0
Bank Sta=321.4,360.1
XS Rating Curve= 0 ,0
Exp/Cntr=0.3,0.1

Type RM Length L Ch R = 1 ,19799   ,321.6,305.8,290.3
XS GIS Cut Line= 4
     1869636.342      480541.045     1869804.675      480429.379
     1870008.009      480407.156      1870129.12       480350.49
#Sta/Elev= 29
       0 1002.16    19.2     993    57.7  975.09    86.6  962.04   105.8  953.59
   134.7  941.05   144.3  936.68   153.9  932.18   163.5  927.53   173.2  922.72
   182.8  918.89   192.4  916.94     202  916.03   211.7  914.93   231.2  912.67
     248  910.59   250.7  910.26   260.4  909.81   270.2  909.94   279.9  910.24
   416.1  914.03   444.8  914.73   454.3  915.01   473.4  915.73     483  917.24
   492.5  920.95   502.1   925.4   521.2  934.58   540.3  944.05
#Mann= 3 , 0 , 0
       0      .1       0     248    .045       0   279.9      .1       0
Bank Sta=248,279.9
XS Rating Curve= 0 ,0
Exp/Cntr=0.3,0.1

Type RM Length L Ch R = 1 ,19493.2 ,340.6,337.6,333.8
XS GIS Cut Line= 2
     1869905.795      480766.237     1870243.669      480521.136
#Sta/Elev= 28
       0  957.41     9.7  953.13    19.4  949.02    29.1  945.11    38.8  941.34
    48.5  937.74    58.2  934.29      68  931.01    77.7  927.87    87.4   924.9
    97.1  922.06   116.5  916.88   135.9  911.94   145.6  909.19   155.3  906.83
     165  905.71   174.7  905.76   184.4  906.08   203.8  906.98   291.2  910.53
   300.9  911.55   310.6  914.22     330  922.39   349.5  930.04   359.2   933.7
   388.3     945     398   948.9   417.4  957.01
#Mann= 3 , 0 , 0
       0      .1       0   155.3    .045       0   184.4      .1       0
Bank Sta=155.3,184.4
XS Rating Curve= 0 ,0
Exp/Cntr=0.3,0.1

Type RM Length L Ch R = 1 ,19155.6 ,371.5,416.5,460.7
XS GIS Cut Line= 2
      1870086.45      481071.227     1870555.735      480641.099
#Sta/Elev= 30
       0  948.86     9.8  946.84    19.6  945.06    58.8  938.69    68.6  936.76
    78.4  934.36    88.1  931.66    97.9  928.49   107.7  924.44   127.3  914.79
   137.1  910.26   146.9  906.48   156.7  904.46   179.7  901.29   186.1  900.54
   195.9  900.24   215.5  900.77   274.2  902.62   293.8  903.54   303.6  904.92
   313.4  908.22   401.5  948.76   430.9  962.02   440.7  966.85   460.3  977.06
   470.1  981.81   558.2 1021.96   597.4 1039.99     617 1049.29   636.6 1059.09
#Mann= 3 , 0 , 0
       0      .1       0   179.7    .045       0   215.5      .1       0
Bank Sta=179.7,215.5
XS Rating Curve= 0 ,0
Exp/Cntr=0.3,0.1

Type RM Length L Ch R = 1 ,18739.1 ,439.6,433.1,425.8
XS GIS Cut Line= 3
     1870077.327      481106.422     1870239.877      481141.007
     1870598.835      481462.407
#Sta/Elev= 30
       0  953.51    19.6   949.4    29.3  946.43    48.9  938.53    68.4  929.78
      88  921.62   127.1  907.02   136.9   904.1   146.6  902.78   156.4  902.44
   215.4  901.74   225.2  901.53   244.8  900.59   254.7  899.93   264.5  898.91
   274.4  897.08   284.2  894.85     294  893.97   303.8  894.36   313.7  895.36
   333.4  897.36   392.4  902.33   402.2  904.58     412  909.14   451.4  930.26
   559.5   989.8   618.5 1021.58   628.3 1026.05   638.2  1029.2     648 1031.22
#Mann= 3 , 0 , 0
       0      .1       0   284.2    .045       0   313.7      .1       0
Bank Sta=284.2,313.7
XS Rating Curve= 0 ,0
Exp/Cntr=0.3,0.1

Type RM Length L Ch R = 1 ,18306.1 ,264.6,249.1,233.5
XS GIS Cut Line= 3
     1869740.919      481345.173     1869961.752      481495.173
     1870189.877      481620.173
#Sta/Elev= 30
       0  964.53    28.6  952.91    47.7   944.8    57.2  940.58    76.3  932.37
    85.8  928.51   114.4   917.4   133.5  910.16     143  906.76   152.6  904.77
   162.1  904.03   228.8  901.27   257.4  899.88     267   899.4   305.5  897.05
   315.1  896.29   324.8  894.97   334.4  892.96     344  891.27   353.7  891.08
   363.3  893.23   372.9  897.68   382.6  902.35   392.2  906.49   430.7   922.7
   469.3  938.75   478.9  942.92   488.6  947.26   498.2  951.75   527.1   965.8
#Mann= 3 , 0 , 0
       0      .1       0   334.4    .045       0   363.3      .1       0
Bank Sta=334.4,363.3
XS Rating Curve= 0 ,0
Exp/Cntr=0.3,0.1