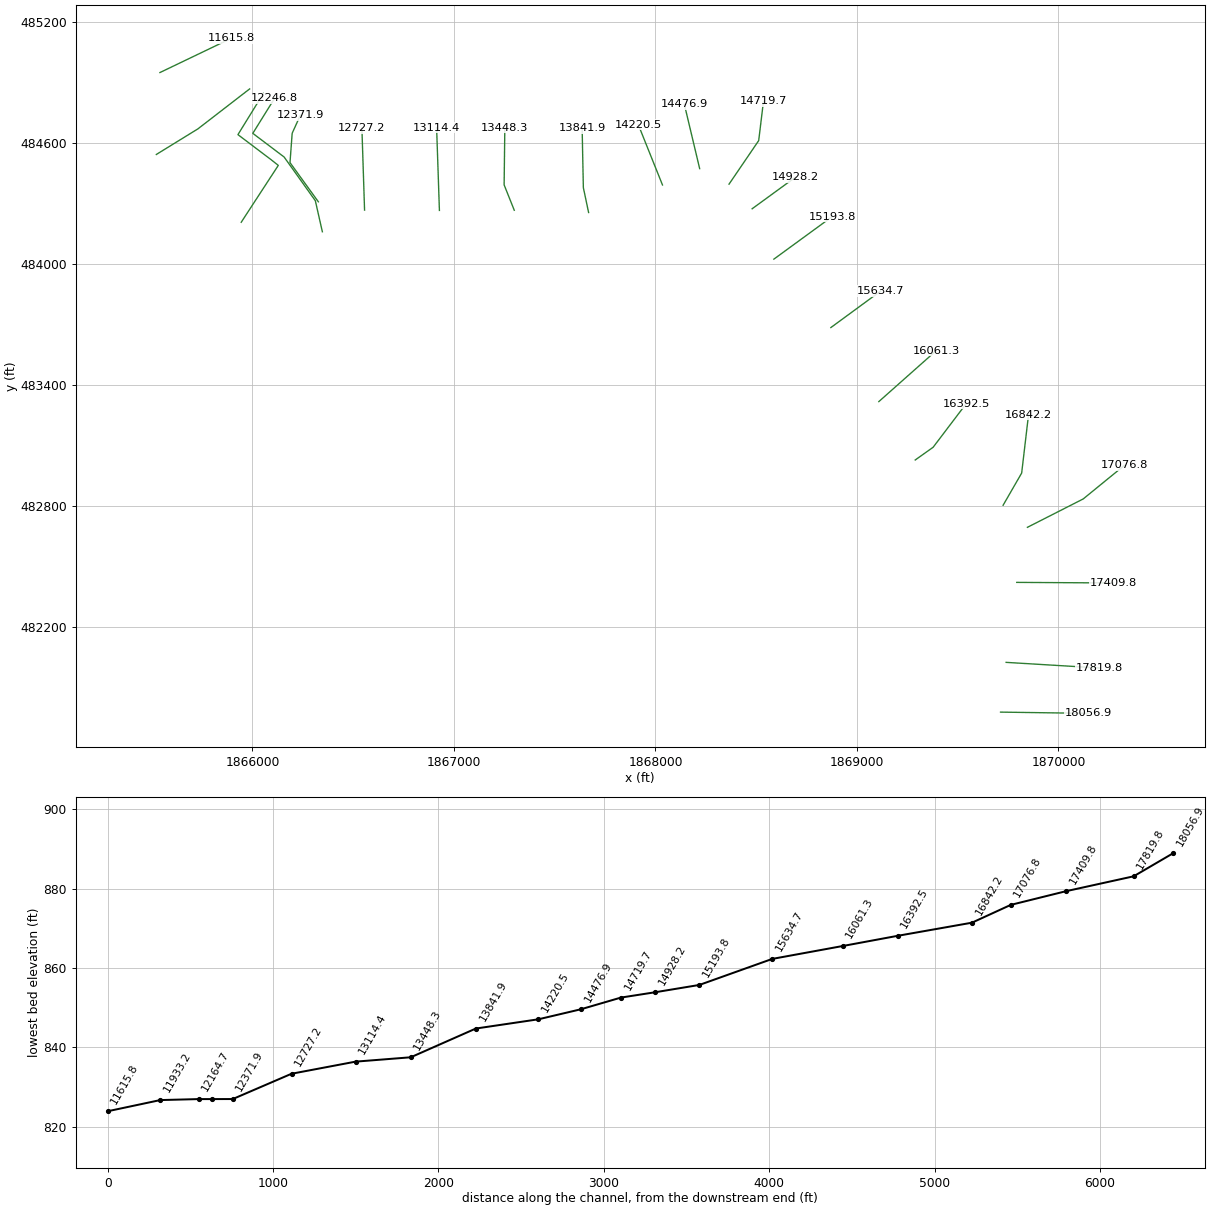
HEC-RAS study MORRISFK.prj: MORRISFK

--- MORRISFK.g01 (geometry) --- (continued)

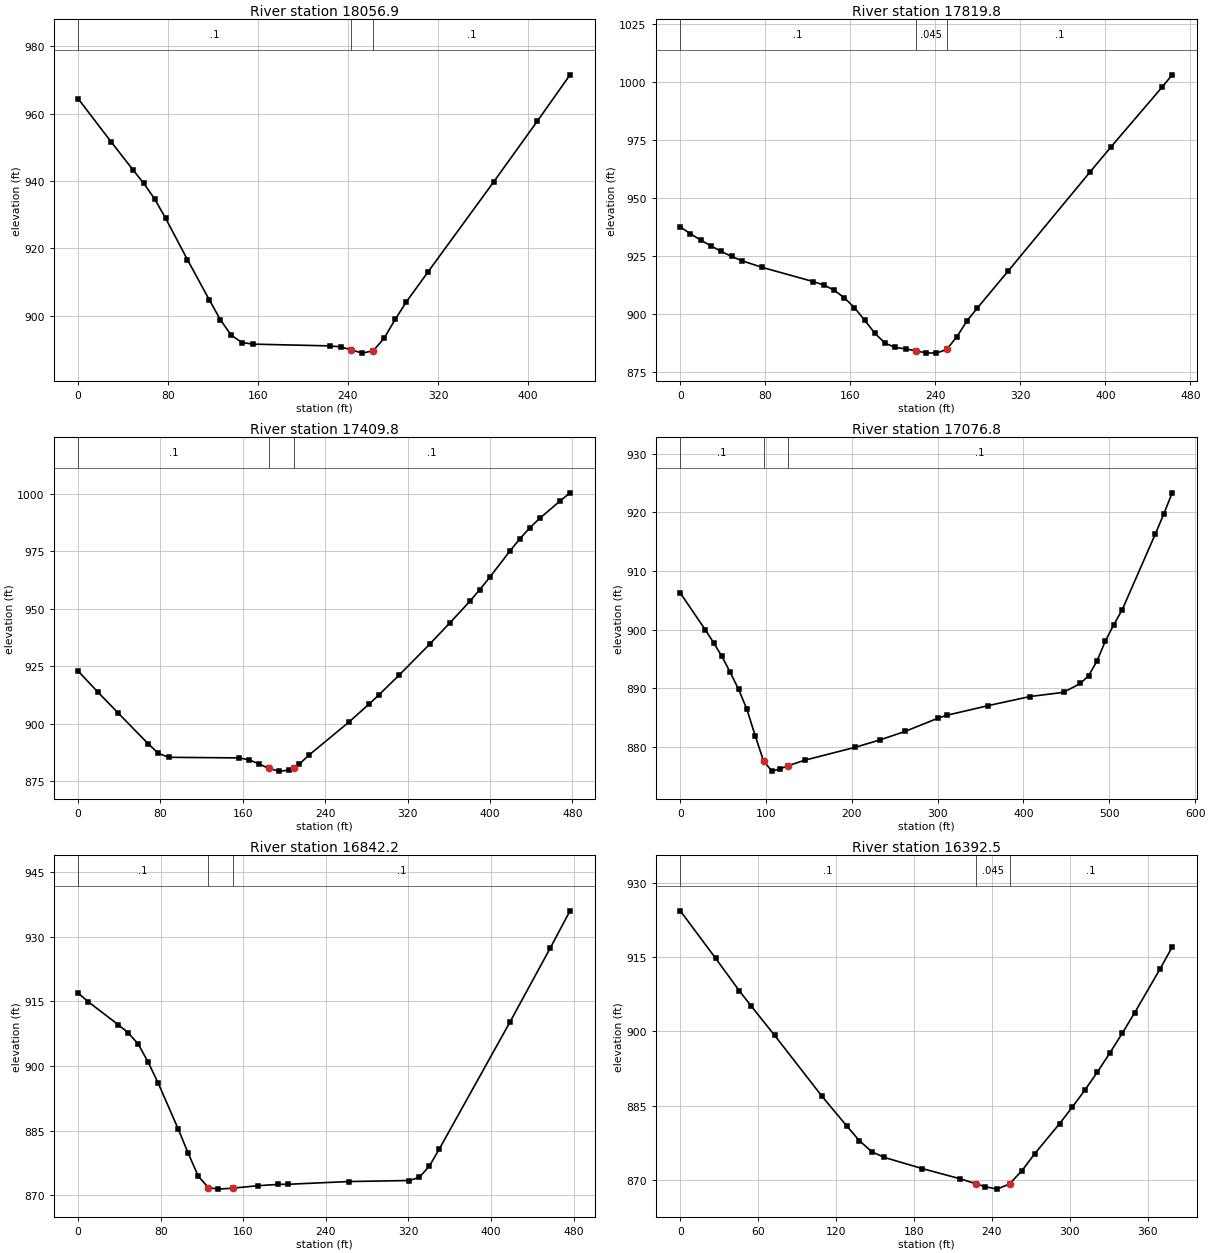
Type RM Length L Ch R = 1 ,18056.9 ,238.4,237.2,235.6
XS GIS Cut Line= 2
     1869712.794      481777.465     1870150.294      481771.215
#Sta/Elev= 24
       0  964.45    29.2  951.69    48.6  943.38    58.3  939.32    68.1  934.64
    77.8  928.94    97.2  916.63   116.7  904.68   126.4  898.86   136.1  894.21
   145.8  892.03   155.6  891.55   223.6  891.03   233.4  890.75   242.7  889.87
   252.8  888.88   262.5   889.6   272.2  893.34     282  898.89   291.7  904.01
   311.1  912.96   369.5   939.7   408.4  957.77   437.5  971.53
#Mann= 3 , 0 , 0
       0      .1       0   242.7    .045       0   262.5      .1       0
Bank Sta=242.7,262.5
XS Rating Curve= 0 ,0
Exp/Cntr=0.3,0.1

Type RM Length L Ch R = 1 ,17819.8 ,408.3,410,411.5
XS GIS Cut Line= 2
     1869740.595      482024.172     1870202.513      481996.387
#Sta/Elev= 30
       0  937.45     9.6   934.5    19.3  931.77    28.9  929.26    38.6  926.89
    48.2  924.74    57.8  922.92    77.1  920.02   125.3  913.89     135  912.43
   144.6  910.26   154.2     907   163.9  902.66   173.5  897.26   183.2  891.58
   192.8  887.36   202.4  885.54   212.1  884.94   221.7  884.08   231.4  883.22
     241  883.11   250.7  884.72   260.3  890.25   269.9  897.11   279.6   902.6
   308.5  918.47   385.6  961.16   404.9  971.73   453.1  997.53   462.8 1002.94
#Mann= 3 , 0 , 0
       0      .1       0   221.7    .045       0   250.7      .1       0
Bank Sta=221.7,250.7
XS Rating Curve= 0 ,0
Exp/Cntr=0.3,0.1

Type RM Length L Ch R = 1 ,17409.8 ,318.5,333.1,347.2
XS GIS Cut Line= 2
      1869793.23      482420.847     1870270.988      482418.021
#Sta/Elev= 30
       0  922.87    19.5  913.56      39  904.55    68.2  891.17      78   887.1
    87.8  885.36     156   885.1   165.8  884.31   175.5  882.54   185.3   880.5
     195  879.35   204.8  879.71   209.2  880.88   214.5  882.28   224.3  886.35
   263.3  900.79   282.8  908.58   292.5  912.66     312  921.19   341.3  934.48
   360.8  943.68   380.3  953.11     390  958.19   399.8  963.64   419.3  974.98
     429  980.37   438.8  985.19   448.5  989.32     468  996.78   477.8 1000.36
#Mann= 3 , 0 , 0
       0      .1       0   185.3    .045       0   209.2      .1       0
Bank Sta=185.3,209.2
XS Rating Curve= 0 ,0
Exp/Cntr=0.3,0.1

Type RM Length L Ch R = 1 ,17076.8 ,216.9,234.6,251.6
XS GIS Cut Line= 3
     1869846.266      482693.993     1870122.932      482834.548
     1870326.821       483000.66
#Sta/Elev= 30
       0  906.28    29.1  900.01    38.8  897.81    48.5  895.45    58.2  892.76
    67.9  889.86    77.6  886.47    87.3  881.94      97  877.67   106.7  875.91
   116.4   876.3   125.2  876.82   145.5  877.79   203.6  879.96   232.7  881.23
   261.8  882.67   300.6  884.95   310.3  885.42     359  887.08   407.7  888.63
   446.7  889.34   466.2  890.85   475.9  892.18   485.6  894.66   495.4  898.09
   505.1  900.84   514.9  903.38   553.8  916.38   563.6  919.78   573.3  923.35
#Mann= 3 , 0 , 0
       0      .1       0      97    .045       0   125.2      .1       0
Bank Sta=97,125.2
XS Rating Curve= 0 ,0
Exp/Cntr=0.3,0.1

Type RM Length L Ch R = 1 ,16842.2 ,453.4,449.6,445.2
XS GIS Cut Line= 3
     1869725.536      482803.482     1869817.654      482963.065
     1869851.821      483253.437
#Sta/Elev= 24
       0  916.97     9.7  914.95    38.8  909.62    48.5  907.73    58.2  905.12
    67.9  900.89    77.6  896.02      97  885.38   106.7  879.71   116.4  874.45
   126.1   871.8   135.8  871.43   149.9  871.66   174.6  872.23     194  872.53
   203.8  872.56   262.2  873.19   320.7  873.43   330.4  874.14   340.2  876.73
   349.9  880.73   418.2  910.14   457.2  927.31   476.6  936.05
#Mann= 3 , 0 , 0
       0      .1       0   126.1    .045       0   149.9      .1       0
Bank Sta=126.1,149.9
XS Rating Curve= 0 ,0
Exp/Cntr=0.3,0.1

Type RM Length L Ch R = 1 ,16392.5 ,336.9,331.3,325.9
XS GIS Cut Line= 3
     1869289.373      483027.882     1869378.262      483091.076
     1869541.457      483306.007
#Sta/Elev= 27
       0   924.3    27.3  914.69    45.4  908.18    54.5  905.11    72.7  899.15
   109.1  886.88   128.3  880.84     138  877.89   147.6  875.65   157.2  874.52
   186.2  872.28   215.1  870.24   227.5  869.22   234.4  868.64     244  868.12
   253.6  869.17   263.3  871.88   272.9  875.24   292.2  881.35   301.8  884.62
   311.5  888.06   321.1  891.68   330.7  895.53   340.4  899.57     350  903.73
   369.3  912.46   378.9  916.98
#Mann= 3 , 0 , 0
       0      .1       0   227.5    .045       0   253.6      .1       0
Bank Sta=227.5,253.6
XS Rating Curve= 0 ,0
Exp/Cntr=0.3,0.1

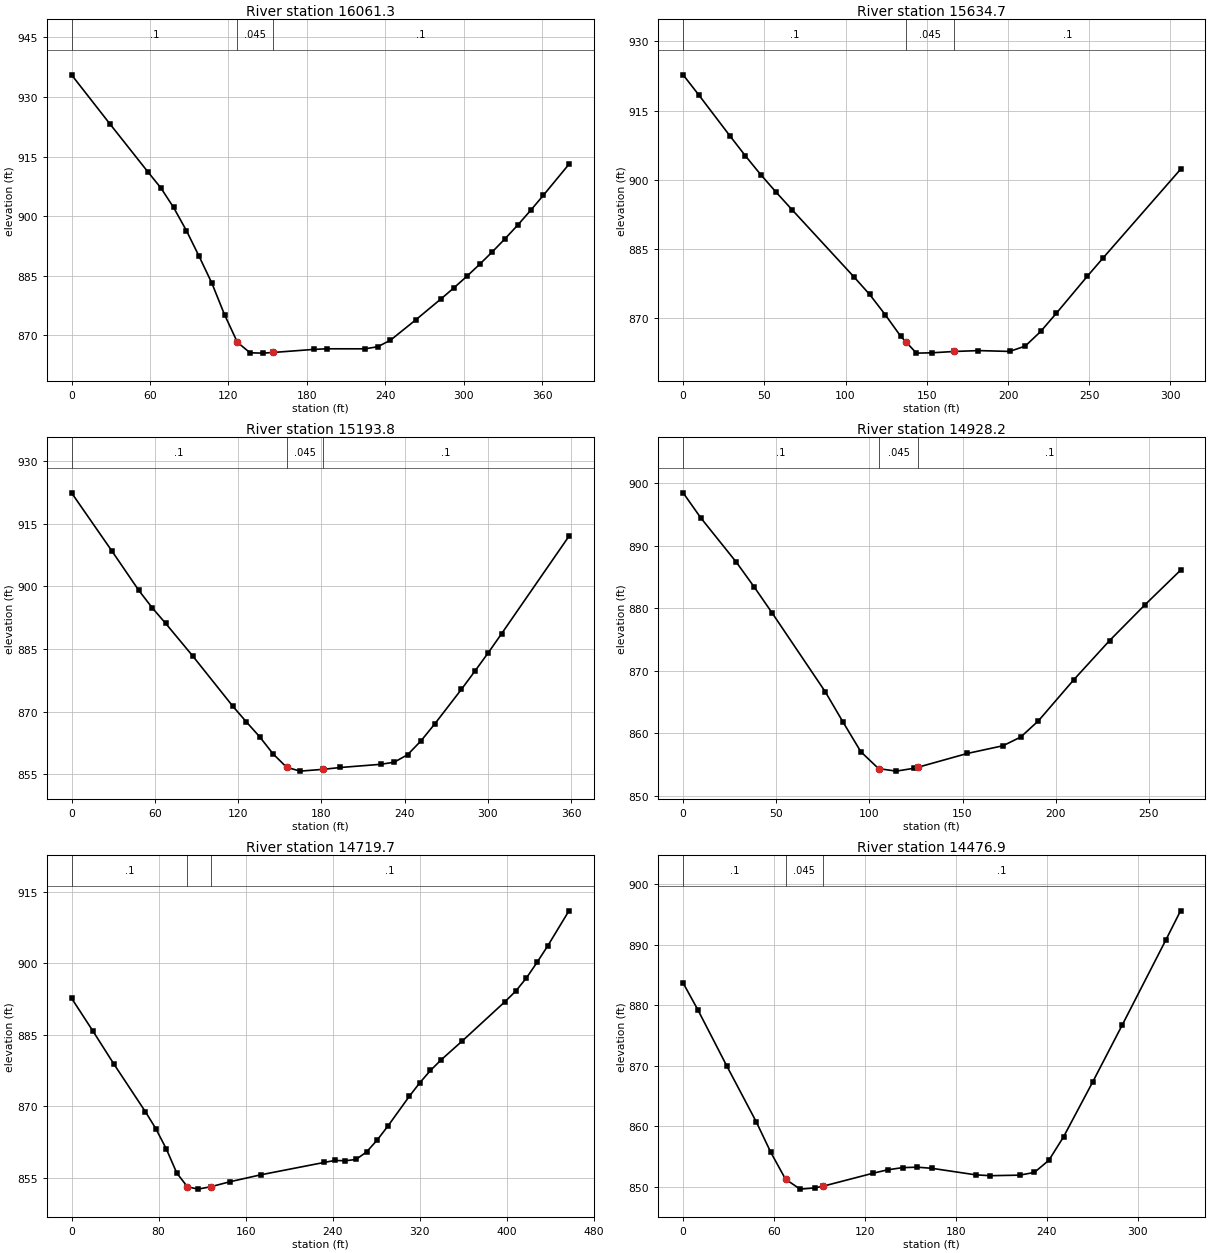
Type RM Length L Ch R = 1 ,16061.3 ,429.3,426.5,423.7
XS GIS Cut Line= 2
     1869108.794      483317.471      1869393.28      483569.844
#Sta/Elev= 29
       0  935.55    29.2  923.26    58.5  911.09    68.3  907.11      78   902.2
    87.8  896.39    97.5  889.93   107.3  883.15     117  875.21   126.8  868.29
   136.5  865.64   146.3  865.56   154.3  865.73   185.3   866.5     195  866.65
   224.3  866.64     234  867.16   243.8   868.8   263.3  873.96   282.8  879.29
   292.5  882.02   302.3   884.9     312  887.89   321.8  891.06   331.5  894.35
   341.3  897.82     351  901.46   360.8  905.28   380.3  913.06
#Mann= 3 , 0 , 0
       0      .1       0   126.8    .045       0   154.3      .1       0
Bank Sta=126.8,154.3
XS Rating Curve= 0 ,0
Exp/Cntr=0.3,0.1

Type RM Length L Ch R = 1 ,15634.7 ,441,441,440.8
XS GIS Cut Line= 2
     1868870.725       483684.67     1869117.778      483865.654
#Sta/Elev= 23
       0  922.75     9.6   918.4    28.7  909.54    38.3  905.17    47.8  901.06
    57.4   897.2      67  893.47   105.3  878.81   114.8  875.06   124.4  870.66
     134  865.94     137  864.81   143.6  862.31   153.1  862.38     167  862.67
   181.8  862.86     201  862.68   210.6  863.84   220.1  867.01   229.7  870.95
   248.8     879   258.4  882.93   306.2  902.23
#Mann= 3 , 0 , 0
       0      .1       0     137    .045       0     167      .1       0
Bank Sta=137,167
XS Rating Curve= 0 ,0
Exp/Cntr=0.3,0.1

Type RM Length L Ch R = 1 ,15193.8 ,265.6,265.6,265.6
XS GIS Cut Line= 2
     1868587.778      484023.948     1868877.421      484235.168
#Sta/Elev= 24
       0  922.34    29.1  908.42    48.4  899.03    58.1  894.85    67.8  891.11
    87.2  883.36   116.3  871.25     126  867.53   135.6  863.96   145.3  859.86
     155  856.68   164.7  855.75   181.4  856.18   193.8  856.62   222.8  857.38
   232.5  857.88   242.2  859.67   251.9  863.01   261.6  866.97     281  875.32
   290.7  879.67   300.4   884.1     310  888.66   358.5  911.95
#Mann= 3 , 0 , 0
       0      .1       0     155    .045       0   181.4      .1       0
Bank Sta=155,181.4
XS Rating Curve= 0 ,0
Exp/Cntr=0.3,0.1

Type RM Length L Ch R = 1 ,14928.2 ,198.1,208.4,218.8
XS GIS Cut Line= 2
     1868480.088      484273.909     1868695.923      484431.146
#Sta/Elev= 20
       0  898.43     9.5  894.42    28.6  887.32    38.2  883.35    47.7  879.25
    76.3  866.61    85.8  861.78    95.4  857.02   104.9  854.32   114.4  853.92
     124  854.38   126.3  854.56   152.6  856.75   171.7  857.98   181.2  859.37
   190.7  861.96   209.8  868.57   228.9   874.8     248  880.55     267  886.05
#Mann= 3 , 0 , 0
       0      .1       0   104.9    .045       0   126.3      .1       0
Bank Sta=104.9,126.3
XS Rating Curve= 0 ,0
Exp/Cntr=0.3,0.1

Type RM Length L Ch R = 1 ,14719.7 ,217.5,242.8,267.9
XS GIS Cut Line= 3
      1868365.27       484395.91     1868512.492      484611.883
     1868536.103      484806.327
#Sta/Elev= 30
       0  892.67    19.4  885.86    38.7  878.92    67.8  868.86    77.4   865.3
    87.1  861.02    96.8  855.92   106.5  853.07   116.2  852.57   128.2  853.08
   145.2   854.1   174.2  855.59   232.3  858.18     242  858.59   251.7  858.53
   261.4   858.8   271.2  860.38     281   862.9   290.8  865.82   310.4  872.04
   320.1  874.91   329.9  877.49   339.7  879.72   359.3  883.72   398.5  891.96
   408.3  894.16   418.1  896.92   427.9   900.2   437.7  903.66   457.2  911.02
#Mann= 3 , 0 , 0
       0      .1       0   106.5    .045       0   128.2      .1       0
Bank Sta=106.5,128.2
XS Rating Curve= 0 ,0
Exp/Cntr=0.3,0.1

Type RM Length L Ch R = 1 ,14476.9 ,250.8,256.4,260.7
XS GIS Cut Line= 2
     1868219.505      484472.791     1868143.385      484792.178
#Sta/Elev= 24
       0  883.69     9.7  879.27      29  869.89    48.3  860.73    57.9  855.68
    67.6  851.26    77.2  849.62    86.9  849.82    92.3   850.1   125.5  852.26
   135.2  852.82   144.8  853.17   154.5  853.25   164.2  853.06   193.1  851.98
   202.8  851.84   222.1  851.93   231.8  852.38   241.4  854.39   251.1  858.27
   270.4  867.37   289.7  876.69   318.7  890.85   328.3  895.62
#Mann= 3 , 0 , 0
       0      .1       0    67.6    .045       0    92.3      .1       0
Bank Sta=67.6,92.3
XS Rating Curve= 0 ,0
Exp/Cntr=0.3,0.1

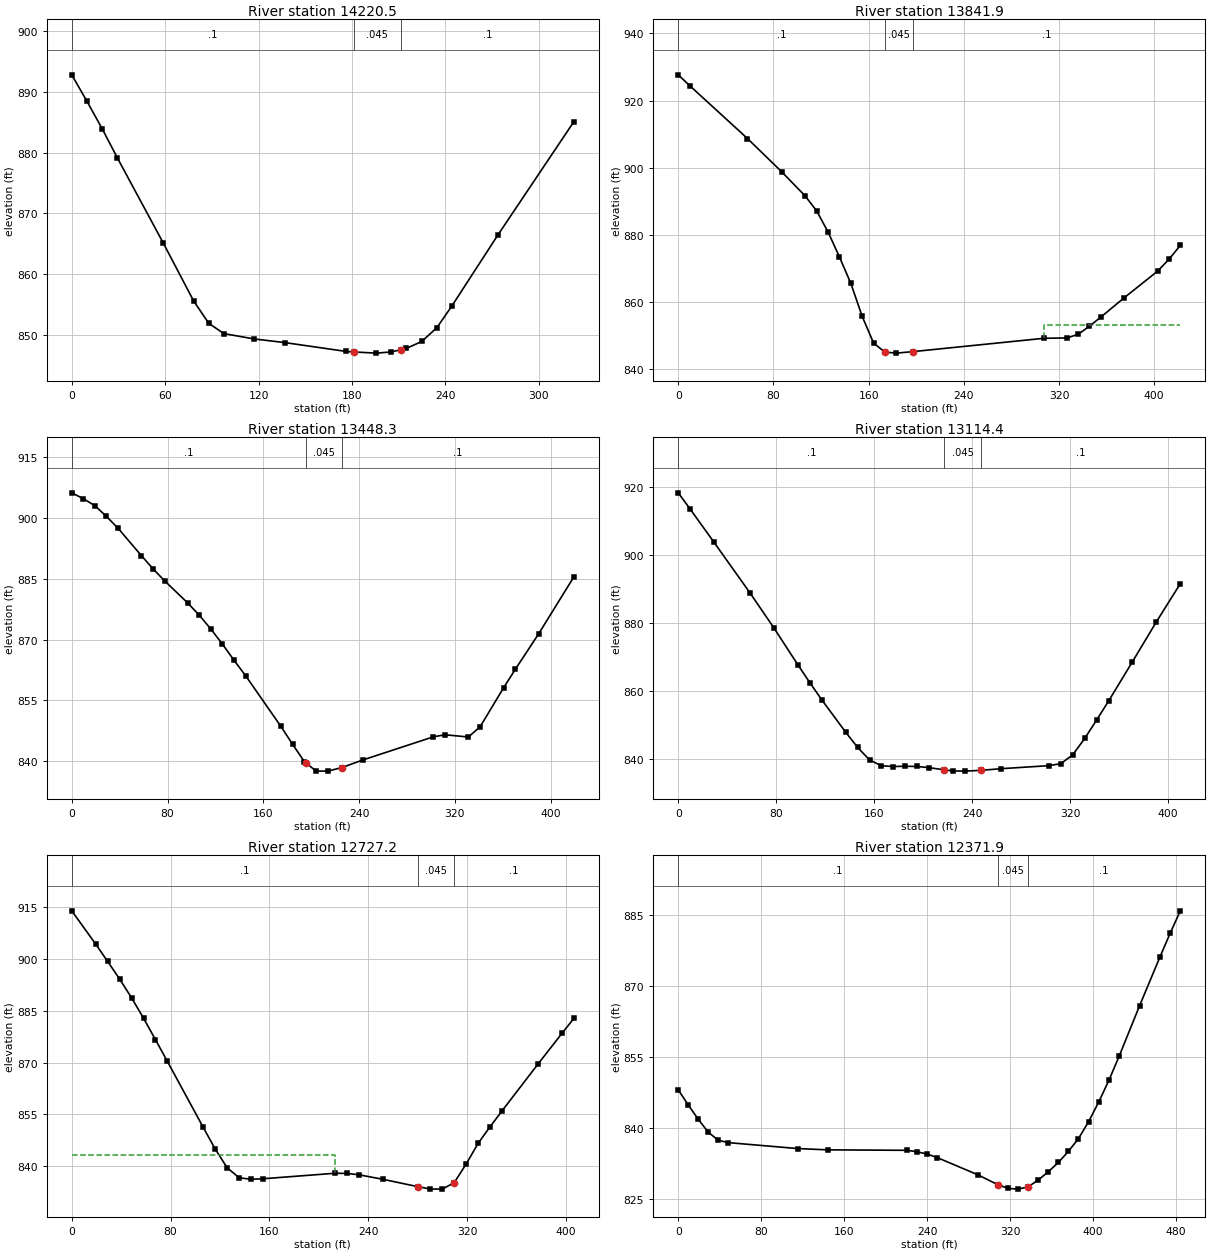
Type RM Length L Ch R = 1 ,14220.5 ,389.5,378.6,367.8
XS GIS Cut Line= 2
     1868034.917       484391.86     1867914.778      484691.165
#Sta/Elev= 21
       0  892.74     9.8  888.38    19.6  883.86    29.3  879.11    58.6  865.24
    78.2  855.69      88  851.99    97.7   850.3   117.3  849.42   136.8  848.83
   175.9  847.39   181.3  847.29   195.5   847.1   205.2  847.29   211.3  847.66
     215  847.88   224.8  849.01   234.6   851.3   244.3  854.89   273.6  866.43
   322.5  885.05
#Mann= 3 , 0 , 0
       0      .1       0   181.3    .045       0   211.3      .1       0
Bank Sta=181.3,211.3
XS Rating Curve= 0 ,0
Exp/Cntr=0.3,0.1

Type RM Length L Ch R = 1 ,13841.9 ,394.1,393.6,392.2
XS GIS Cut Line= 3
      1867668.25      484255.228     1867642.208      484378.491
     1867636.132      484674.498
#Sta/Elev= 23
       0  927.68     9.7  924.44    58.2   908.7    87.2  898.71   106.6  891.62
   116.3  887.17     126  880.82   135.5  873.41   145.1  865.52   154.6  855.73
   164.2  847.76   173.7  845.07   183.3  844.77     197  845.21   307.4  849.19
   326.6   849.3   336.1  850.37   345.6  852.78   355.2   855.5   374.3  861.11
     403  869.22   412.5  872.75     422  876.86
#Mann= 3 , 0 , 0
       0      .1       0   173.7    .045       0     197      .1       0
#XS Ineff= 2 , 0
                          307.69          853.12
Permanent Ineff=
       F       F
Bank Sta=173.7,197
XS Rating Curve= 0 ,0
Exp/Cntr=0.3,0.1

Type RM Length L Ch R = 1 ,13448.3 ,332.5,333.9,335.2
XS GIS Cut Line= 3
     1867299.327      484266.512     1867248.979       484392.38
     1867252.452      484676.235
#Sta/Elev= 30
       0   906.2     9.7  904.75    19.4  903.01      29  900.37    38.7  897.45
    58.1  890.72    67.8  887.48    77.5   884.5    96.8  879.04   106.5  876.01
   116.2  872.58   125.9  868.85   135.6  864.86   145.4     861   174.7  848.56
   184.5  844.13   194.3  839.87   195.7  839.54   204.1  837.54   213.9  837.53
   225.7  838.42   243.2  840.29     302  845.99   311.8   846.5   331.3  845.95
   341.1  848.47   360.7   858.1   370.5  862.64   390.1  871.46   419.4  885.46
#Mann= 3 , 0 , 0
       0      .1       0   195.7    .045       0   225.7      .1       0
Bank Sta=195.7,225.7
XS Rating Curve= 0 ,0
Exp/Cntr=0.3,0.1

Type RM Length L Ch R = 1 ,13114.4 ,386.8,387.2,386.7
XS GIS Cut Line= 2
     1866927.799      484265.644      1866913.91      484675.366
#Sta/Elev= 30
       0  918.27     9.8  913.46    29.3  903.69    58.6  888.84    78.1  878.56
    97.6  867.75   107.4  862.48   117.1  857.46   136.6  847.94   146.4  843.45
   156.2  839.73   165.9  838.01   175.7  837.79   185.5  837.86   195.2   837.8
     205  837.44   217.3  836.81   224.5  836.49   234.3  836.43   247.3  836.67
   263.5  837.14   302.6  838.04   312.4  838.62   322.1  841.21   331.9  846.03
   341.6  851.42   351.4  857.02   370.9   868.6   390.4   880.3     410  891.56
#Mann= 3 , 0 , 0
       0      .1       0   217.3    .045       0   247.3      .1       0
Bank Sta=217.3,247.3
XS Rating Curve= 0 ,0
Exp/Cntr=0.3,0.1

Type RM Length L Ch R = 1 ,12727.2 ,358.2,355.3,351.8
XS GIS Cut Line= 2
     1866556.291      484267.071     1866543.096      484673.321
#Sta/Elev= 29
       0  913.88    19.4  904.24      29  899.27    38.7  894.17    48.4  888.73
    58.1  882.82    67.7  876.65    77.4  870.34   106.4  851.26   116.1     845
   125.8  839.56   135.5  836.67   145.2  836.23   154.8  836.38   212.9  837.96
   222.6  837.93   232.3  837.54   251.6  836.25   280.6  834.06   290.3  833.42
     300  833.38   309.7  835.27   319.4  840.69     329  846.63   338.7  851.44
   348.4  856.04   377.4  869.52   396.8  878.41   406.5  882.75
#Mann= 3 , 0 , 0
       0      .1       0   280.6    .045       0   309.7      .1       0
#XS Ineff= 2 , 0
          213.37  843.34
Permanent Ineff=
       F       F
Bank Sta=280.6,309.7
XS Rating Curve= 0 ,0
Exp/Cntr=0.3,0.1

Type RM Length L Ch R = 1 ,12371.9 ,79,125,163.7
XS GIS Cut Line= 4
     1866327.002      484308.254     1866186.224      484502.756
     1866197.002      484648.254     1866237.557      484737.698
#Sta/Elev= 30
       0  847.99     9.6  844.81    19.2   841.8    28.8  839.08    38.4  837.35
      48  836.84   115.2  835.58   144.1  835.31   220.9  835.21   230.5  834.89
   240.1  834.42   249.8  833.67   288.7  830.06   308.2  827.95   317.9  827.18
   327.6  827.01   337.4  827.49   347.1  828.92   356.8  830.67   366.6  832.64
   376.3     835     386  837.69   395.8  841.28   405.6  845.45   415.5  850.09
   425.3  855.14   444.9  865.75   464.6  876.08   474.4  881.07   484.2  885.81
#Mann= 3 , 0 , 0
       0      .1       0   308.2    .045       0   337.4      .1       0
Bank Sta=308.2,337.4
XS Rating Curve= 0 ,0
Exp/Cntr=0.3,0.1

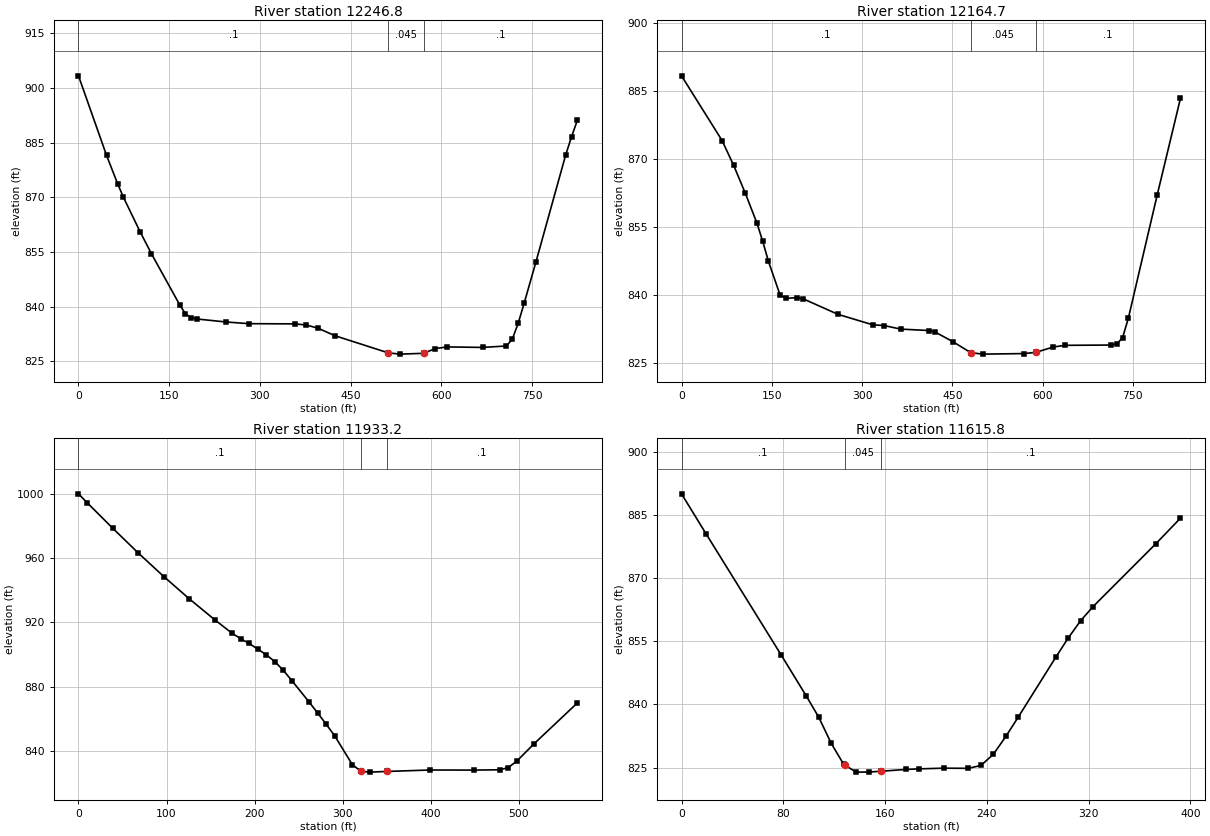
Type RM Length L Ch R = 1 ,12246.8 ,82.7,82.1,104.1
XS GIS Cut Line= 5
     1866346.847       484159.61     1866311.987      484313.598
      1866156.93      484530.561     1866001.571      484647.899
     1866110.335      484822.698
#Sta/Elev= 30
       0  903.29    46.4  881.48      65   873.6    74.3     870   102.2  860.44
   120.7   854.5   167.4   840.5   176.9  838.06   186.5  836.95     196  836.63
   243.6  835.82   281.7  835.35   357.9  835.29   376.9  834.98     396  834.11
   424.6  832.02   512.2  827.35   531.6     827   570.6  827.22     590  828.52
   609.5  828.98   668.3  828.84   707.5  829.23   717.3  831.06   727.1  835.45
   736.9  840.91   756.5  852.29   805.5  881.51   815.3  886.58   825.1  891.17
#Mann= 3 , 0 , 0
       0      .1       0   512.2    .045       0   570.6      .1       0
Bank Sta=512.2,570.6
XS Rating Curve= 0 ,0
Exp/Cntr=0.3,0.1

Type RM Length L Ch R = 1 ,12164.7 ,302.1,231.5,145.5
XS GIS Cut Line= 5
      1865944.07      484206.832     1866128.215      484488.973
     1866092.405      484517.205     1865927.821      484641.511
     1866054.224      484846.031
#Sta/Elev= 30
       0  888.29    67.4  874.04    86.6  868.59   105.9  862.47   125.1  855.94
   134.8  851.92   144.4  847.46   163.6  840.09   173.3  839.27   192.5  839.46
   202.2  839.18   259.9  835.77   317.7  833.46   336.9  833.29   364.3  832.51
     412  832.19   421.8  831.84   451.3  829.72   480.7  827.32   500.4     827
   569.1  827.12   588.8  827.39   617.6  828.56   636.9  828.94   713.8     829
   723.4  829.24     733  830.61   742.6  834.92   790.7  862.14   829.2  883.35
#Mann= 3 , 0 , 0
       0      .1       0   480.7    .045       0   588.8      .1       0
Bank Sta=480.7,588.8
XS Rating Curve= 0 ,0
Exp/Cntr=0.3,0.1

Type RM Length L Ch R = 1 ,11933.2 ,323.6,317.4,310.8
XS GIS Cut Line= 3
     1865522.727      484543.035     1865729.098      484669.962
     1865985.995      484868.254
#Sta/Elev= 30
       0 1000.17     9.7  994.71    38.8  978.79    67.8  963.36    96.9  948.63
     126  934.68   155.1  921.55   174.4  913.31   184.1  909.95   193.8  906.91
   203.5  903.48   213.2  899.92   222.9  895.68   232.6  890.23   242.3  883.84
     262  870.41   271.8  863.54   281.6  856.45   291.4  849.06   311.1  831.41
     321  827.22   330.8  826.75   350.4  827.18   399.6  828.08   448.8  828.01
   478.3  828.21   488.1  829.53     498  833.66   517.6  844.46   566.8  869.91
#Mann= 3 , 0 , 0
       0      .1       0     321    .045       0   350.4      .1       0
Bank Sta=321,350.4
XS Rating Curve= 0 ,0
Exp/Cntr=0.3,0.1

Type RM Length L Ch R = 1 ,11615.8 ,323.5,321.5,319.5
XS GIS Cut Line= 2
     1865540.797      484949.385     1865894.522      485119.039
#Sta/Elev= 25
       0     890    19.6  880.36    78.5  851.68    98.1  842.01   107.9  836.97
   117.7  830.78   127.5  825.78   128.3  825.63   137.3  823.94   147.1  823.96
   156.9  824.15   176.5  824.58   186.4  824.71     206  824.88   225.6  824.84
   235.4  825.53   245.2  828.17     255  832.41   264.8  837.03   294.2  851.18
     304  855.76   313.8  859.88   323.6  863.24   372.7  878.08   392.3  884.23
#Mann= 3 , 0 , 0
       0      .1       0   128.3    .045       0   156.9      .1       0
Bank Sta=128.3,156.9
XS Rating Curve= 0 ,0
Exp/Cntr=0.3,0.1