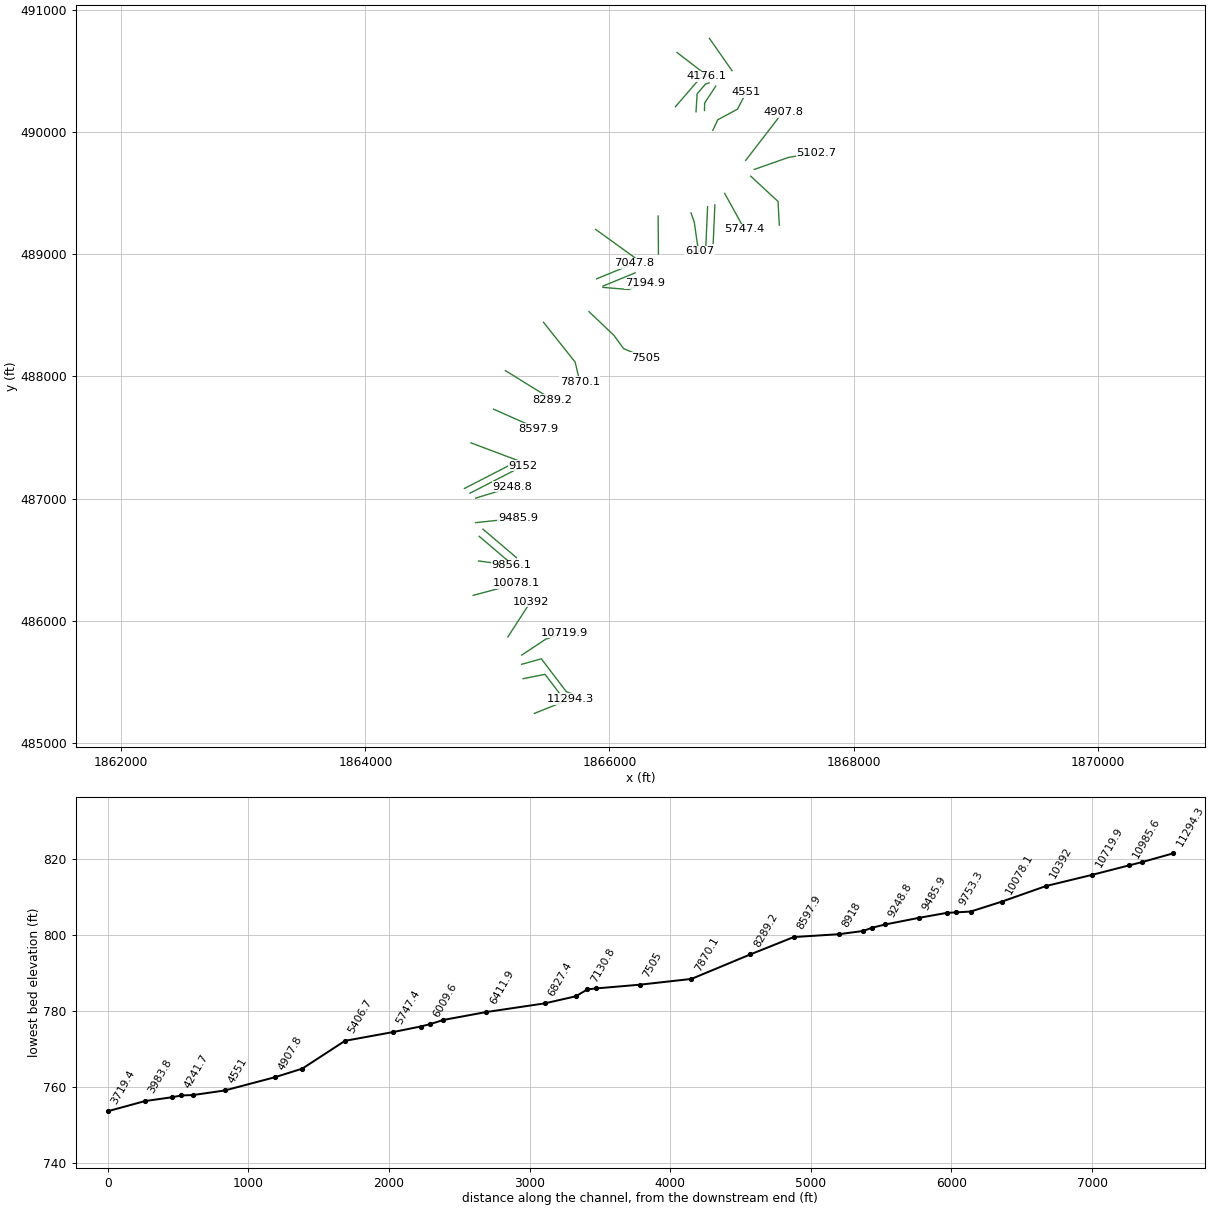
HEC-RAS study MORRISFK.prj: MORRISFK

--- MORRISFK.g01 (geometry) --- (continued)

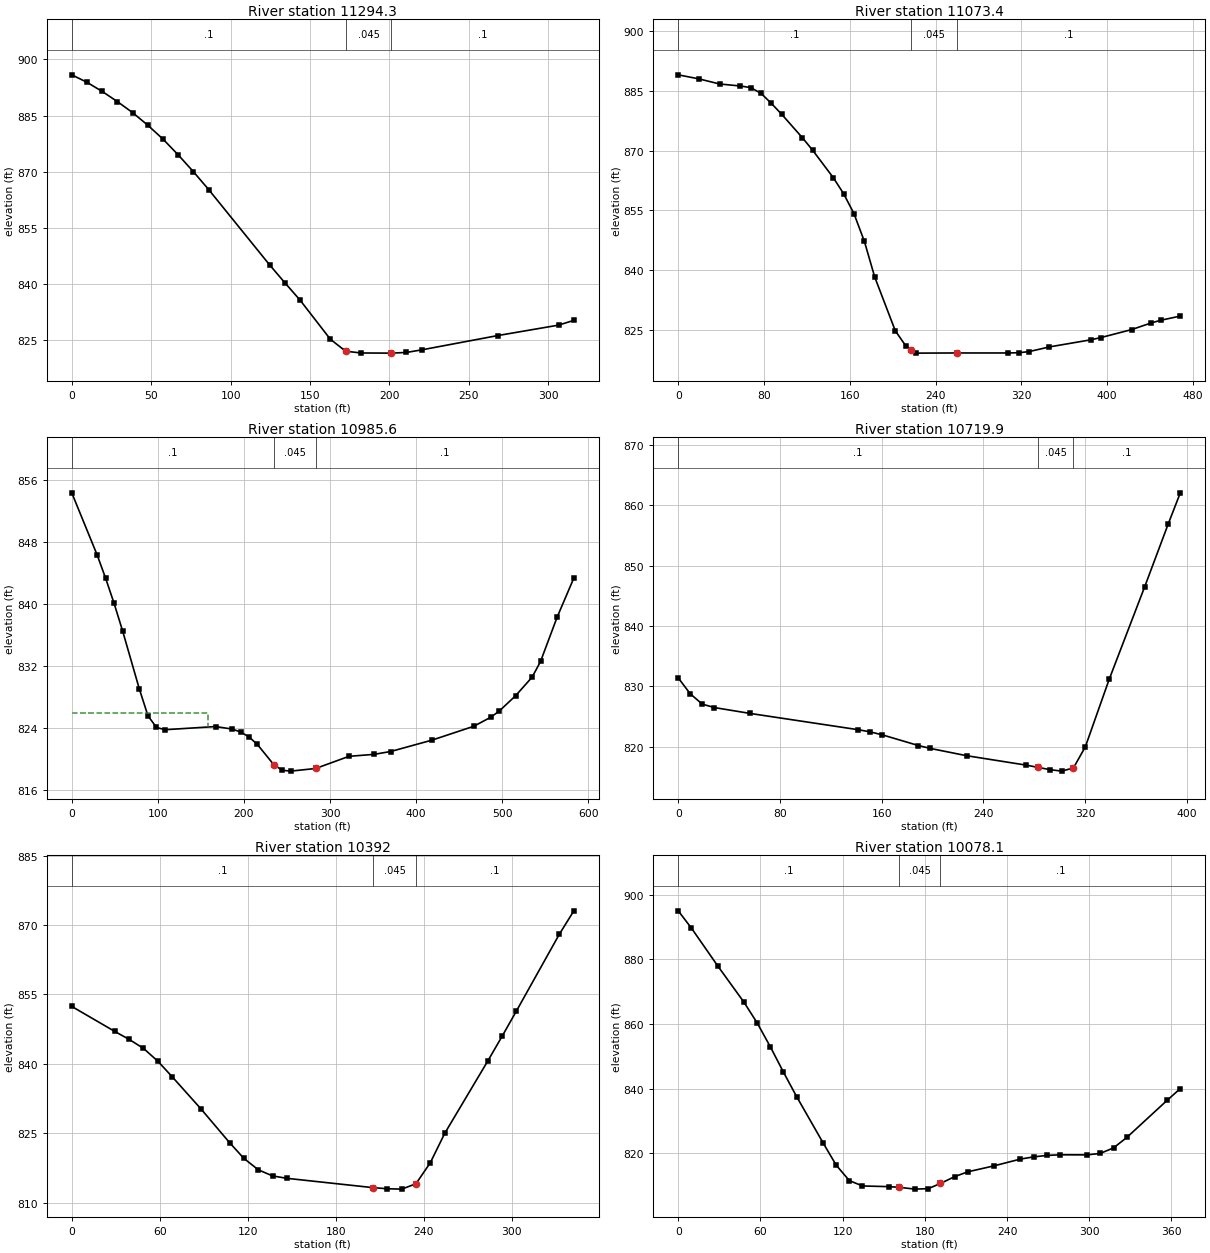
Type RM Length L Ch R = 1 ,11294.3 ,271.2,220.9,166
XS GIS Cut Line= 2
     1865384.624      485243.112     1865678.086      485360.611
#Sta/Elev= 22
       0  895.87     9.6  893.87    19.2  891.42    28.7  888.73    38.3  885.78
    47.9   882.4    57.5  878.68      67   874.5    76.6  869.99    86.2  865.23
   124.5  845.15   134.1  840.38   143.7  835.73   162.8  825.27   172.4  822.08
     182   821.6   201.2  821.56   210.7  821.74   220.3  822.43   268.2  826.25
   306.5  829.04   316.1  830.31
#Mann= 3 , 0 , 0
       0      .1       0   172.4    .045       0   201.2      .1       0
Bank Sta=172.4,201.2
XS Rating Curve= 0 ,0
Exp/Cntr=0.3,0.1

Type RM Length L Ch R = 1 ,11073.4 ,81.9,87.8,92.4
XS GIS Cut Line= 4
     1865292.262      485527.036     1865471.981      485562.707
       1865617.2      485371.978     1865660.242      485358.031
#Sta/Elev= 30
       0  888.96    19.3  887.94    38.6  886.67    57.9  886.16    67.5  885.77
    77.2  884.32    86.8  881.82    96.4   879.1   115.7  873.23   125.4  870.06
   144.6   863.2   154.3  859.16   163.9  854.18   173.6  847.24   183.2  838.34
   202.4  824.86     212  821.15   217.4  820.09   221.6  819.26   259.9   819.3
   307.9   819.3   317.5  819.36   327.1  819.64   346.2  820.82   384.6  822.59
   394.2  823.16     423  825.17     441  826.82   450.1   827.5   468.2  828.54
#Mann= 3 , 0 , 0
       0      .1       0   217.4    .045       0   259.9      .1       0
Bank Sta=217.4,259.9
XS Rating Curve= 0 ,0
Exp/Cntr=0.3,0.1

Type RM Length L Ch R = 1 ,10985.6 ,222,265.7,314.4
XS GIS Cut Line= 4
     1865280.727      485644.571     1865441.689      485689.597
     1865646.871      485420.113     1865719.787      485394.419
#Sta/Elev= 30
       0  854.33    29.5  846.31    39.3  843.32    49.2  840.06      59  836.54
    78.6  828.99    88.5  825.58    98.3  824.08   108.2  823.78   167.1  824.19
   186.5  823.86   196.2  823.48   205.8  822.86   215.5  821.89   234.9  819.24
   244.6  818.55   254.2  818.44   283.3  818.78     322  820.35     351   820.6
   370.4  820.97   418.8  822.45   467.1  824.23   486.5  825.38   496.2  826.15
   515.5  828.16   534.8  830.57   544.5  832.58   563.8   838.3   583.2  843.34
#Mann= 3 , 0 , 0
       0      .1       0   234.9    .045       0   283.3      .1       0
#XS Ineff= 2 , 0
          157.69  825.94
Permanent Ineff=
       F       F
Bank Sta=234.9,283.3
XS Rating Curve= 0 ,0
Exp/Cntr=0.3,0.1

Type RM Length L Ch R = 1 ,10719.9 ,307.8,327.9,347.6
XS GIS Cut Line= 3
     1865281.039      485720.191     1865478.222      485850.315
     1865627.775      485903.455
#Sta/Elev= 21
       0  831.38     9.4  828.75    18.9  827.03    28.4  826.46    56.7  825.48
   141.8  822.78   151.2  822.42   160.6  821.93     189  820.16   198.4  819.68
   226.8  818.48   273.6  816.92   282.9  816.55   292.3  816.17   301.6  815.92
   310.9  816.44   320.3  819.96     339  831.12     367   846.5   385.6  856.96
     395  862.06
#Mann= 3 , 0 , 0
       0      .1       0   282.9    .045       0   310.9      .1       0
Bank Sta=282.9,310.9
XS Rating Curve= 0 ,0
Exp/Cntr=0.3,0.1

Type RM Length L Ch R = 1 ,10392   ,336,313.9,291.5
XS GIS Cut Line= 2
     1865167.693      485869.108     1865353.805      486156.608
#Sta/Elev= 23
       0  852.42    29.4  847.01    39.1  845.31    48.9  843.37    58.7   840.6
    68.5  837.24    88.1  830.31   107.6  823.03   117.4  819.62   127.2  817.16
     137  815.83   146.8  815.31   205.5   813.3   215.3  813.06   225.1  812.98
   234.8  814.14   244.6  818.69   254.4  825.01   283.8  840.65   293.6     846
   303.3  851.42   332.7  868.06   342.5  873.06
#Mann= 3 , 0 , 0
       0      .1       0   205.5    .045       0   234.8      .1       0
Bank Sta=205.5,234.8
XS Rating Curve= 0 ,0
Exp/Cntr=0.3,0.1

Type RM Length L Ch R = 1 ,10078.1 ,233.8,222.1,210
XS GIS Cut Line= 3
     1864883.053      486208.615     1865133.666      486275.358
     1865235.367      486309.056
#Sta/Elev= 30
       0     895     9.6  889.67    28.8  877.97      48  866.71    57.6  860.33
    67.2  852.95    76.8  845.08    86.4  837.53   105.7  823.22   115.3   816.3
   124.9  811.52   134.5  809.86   153.7  809.65   161.4  809.44   172.9  808.88
   182.5  809.03   191.4  810.63   201.7  812.73   211.3  814.23   230.5  816.08
   249.7  818.17   259.4  818.86   269.1  819.31   278.8   819.5   298.3  819.48
     308  819.92   317.8  821.65   327.5  824.89   356.8  836.33   366.5     840
#Mann= 3 , 0 , 0
       0      .1       0   161.4    .045       0   191.4      .1       0
Bank Sta=161.4,191.4
XS Rating Curve= 0 ,0
Exp/Cntr=0.3,0.1

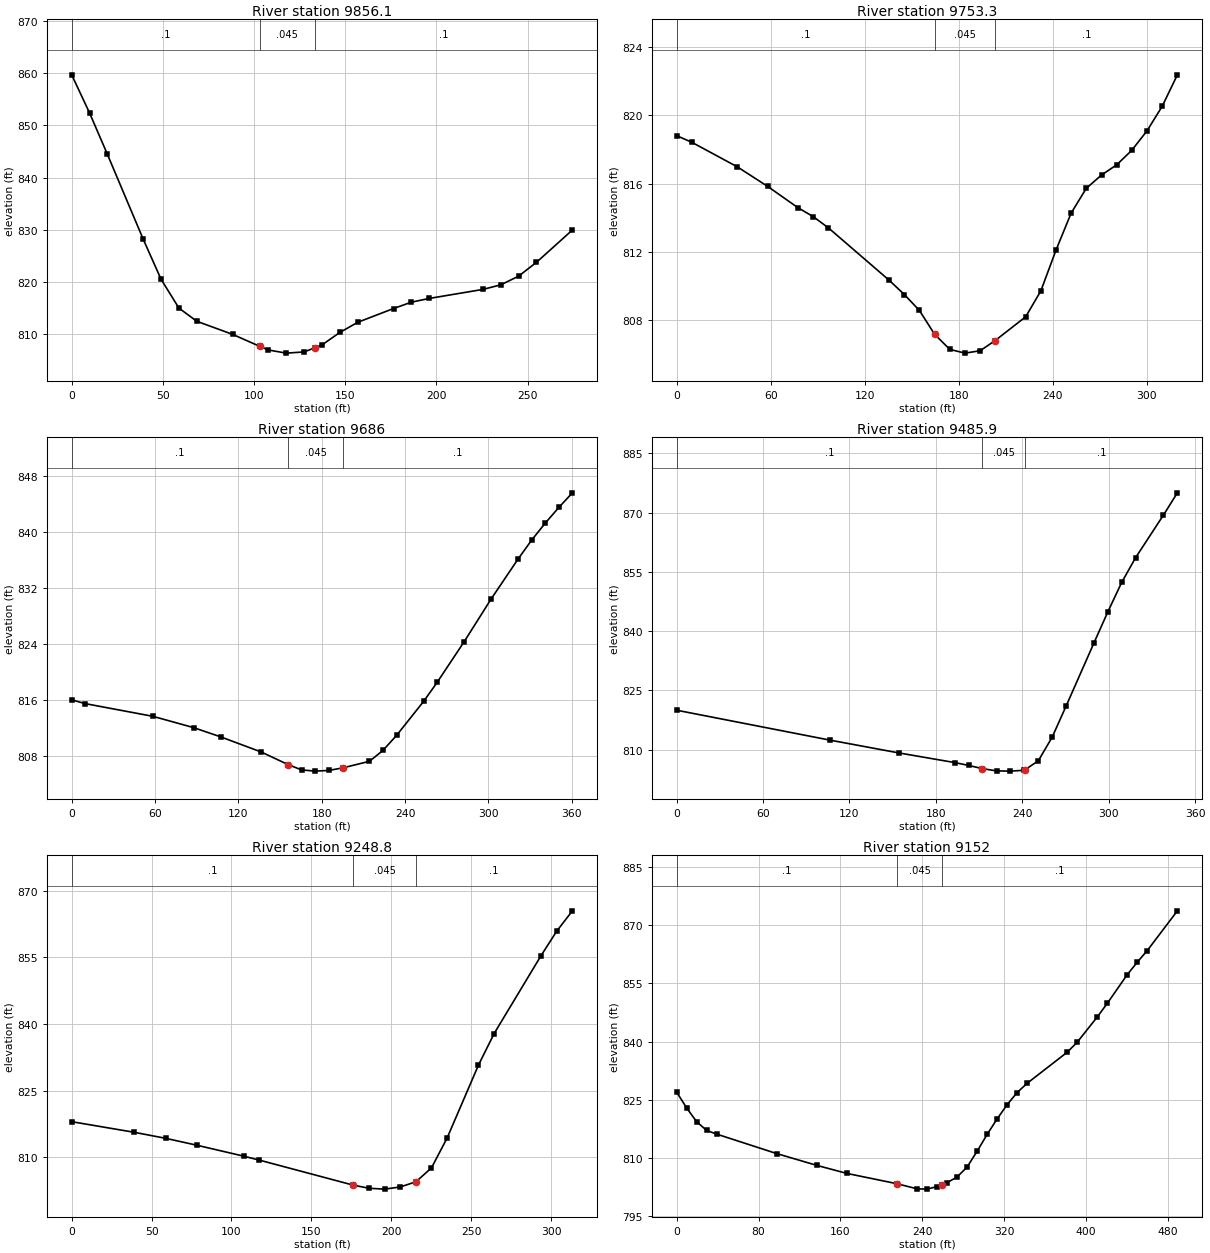
Type RM Length L Ch R = 1 ,9856.1  ,120.2,102.8,85.2
XS GIS Cut Line= 2
     1864926.854      486490.075     1865198.935       486453.33
#Sta/Elev= 24
       0  859.73     9.8   852.4    19.6  844.44    39.2  828.16      49  820.46
    58.8  814.91    68.6  812.38    88.2  809.87   103.3  807.54   107.9  806.86
   117.7  806.26   127.5  806.49   133.3  807.29   137.3  807.85   147.1  810.24
   156.9  812.19   176.5  814.83   186.3  816.05   196.1  816.77   225.5   818.5
   235.3  819.38   245.1  821.05   254.9  823.71   274.6  829.92
#Mann= 3 , 0 , 0
       0      .1       0   103.3    .045       0   133.3      .1       0
Bank Sta=103.3,133.3
XS Rating Curve= 0 ,0
Exp/Cntr=0.3,0.1

Type RM Length L Ch R = 1 ,9753.3  ,67.1,67.3,67.6
XS GIS Cut Line= 2
     1864932.258      486691.461     1865175.718      486484.752
#Sta/Elev= 26
       0  818.81     9.7  818.42    38.7  816.98    58.1  815.83    77.4  814.58
    87.1  814.06    96.8   813.4   135.5  810.33   145.2  809.49   154.8  808.56
   164.5  807.16   174.2  806.27   183.9  806.05   193.6  806.19   203.2  806.79
   222.6  808.18   232.3   809.7     242   812.1   251.6  814.26   261.3  815.72
     271   816.5   280.7   817.1   290.3  817.95     300  819.09   309.7  820.53
   319.4  822.38
#Mann= 3 , 0 , 0
       0      .1       0   164.5    .045       0   203.2      .1       0
Bank Sta=164.5,203.2
XS Rating Curve= 0 ,0
Exp/Cntr=0.3,0.1

Type RM Length L Ch R = 1 ,9686    ,175.5,200.1,224.5
XS GIS Cut Line= 2
     1864963.369       486750.35     1865238.108      486517.084
#Sta/Elev= 23
       0  816.08     9.7  815.54    58.4  813.73    87.7  812.12   107.2   810.8
   136.4  808.64   155.8  806.84   165.5  806.08   175.3  805.91   185.1  806.01
   195.5  806.39   214.3  807.31     224  808.86   233.8     811   253.3  815.86
     263  818.56   282.5  824.38     302   830.5   321.4   836.2   331.2   838.9
   340.9   841.3   350.7  843.54   360.4  845.61
#Mann= 3 , 0 , 0
       0      .1       0   155.8    .045       0   195.5      .1       0
Bank Sta=155.8,195.5
XS Rating Curve= 0 ,0
Exp/Cntr=0.3,0.1

Type RM Length L Ch R = 1 ,9485.9  ,231.2,237.1,242.8
XS GIS Cut Line= 2
     1864903.847       486803.68     1865249.595      486840.238
#Sta/Elev= 19
       0     820   106.2  812.45   154.5  809.18   193.2  806.75   202.8  806.03
     212  805.24   222.1  804.65   231.8  804.59   241.4  804.81     242  804.96
   251.1  807.19   260.8  813.21   270.4  821.03   289.7  836.97   299.4  844.88
     309  852.32   318.7   858.6     338  869.36   347.7     875
#Mann= 3 , 0 , 0
       0      .1       0     212    .045       0     242      .1       0
Bank Sta=212,242
XS Rating Curve= 0 ,0
Exp/Cntr=0.3,0.1

Type RM Length L Ch R = 1 ,9248.8  ,90.7,96.8,102.4
XS GIS Cut Line= 2
     1864903.282      487003.918     1865202.931        487095.7
#Sta/Elev= 18
       0  818.03    39.2  815.64    58.8  814.29    78.4  812.73   107.7  810.27
   117.5  809.38   176.3  803.75   186.1  803.05   195.9  802.86   205.7  803.35
   215.5  804.52   225.2  807.65     235  814.38   254.6  830.76   264.4  837.85
   293.8   855.4   303.6   860.9   313.4  865.46
#Mann= 3 , 0 , 0
       0      .1       0   176.3    .045       0   215.5      .1       0
Bank Sta=176.3,215.5
XS Rating Curve= 0 ,0
Exp/Cntr=0.3,0.1

Type RM Length L Ch R = 1 ,9152    ,59.5,59,58.5
XS GIS Cut Line= 2
     1864856.771      487044.259     1865292.188       487267.87
#Sta/Elev= 30
       0  826.98     9.8  822.88    19.6  819.33    29.4  817.09    39.2  816.15
    97.9  811.13     137   808.1   166.4  806.03   215.4  803.37     235  802.06
   244.7  801.98   254.5  802.63   259.4  803.13   264.3  803.63   274.1   805.1
   283.9  807.66   293.7  811.73   303.5  816.08   313.3  820.08   323.1  823.76
   332.8  826.86   342.6  829.25   381.8  837.26   391.6  839.85   411.2  846.35
     421  849.87   440.5  857.26   450.3  860.47   460.1  863.47   489.5   873.7
#Mann= 3 , 0 , 0
       0      .1       0   215.4    .045       0   259.4      .1       0
Bank Sta=215.4,259.4
XS Rating Curve= 0 ,0
Exp/Cntr=0.3,0.1

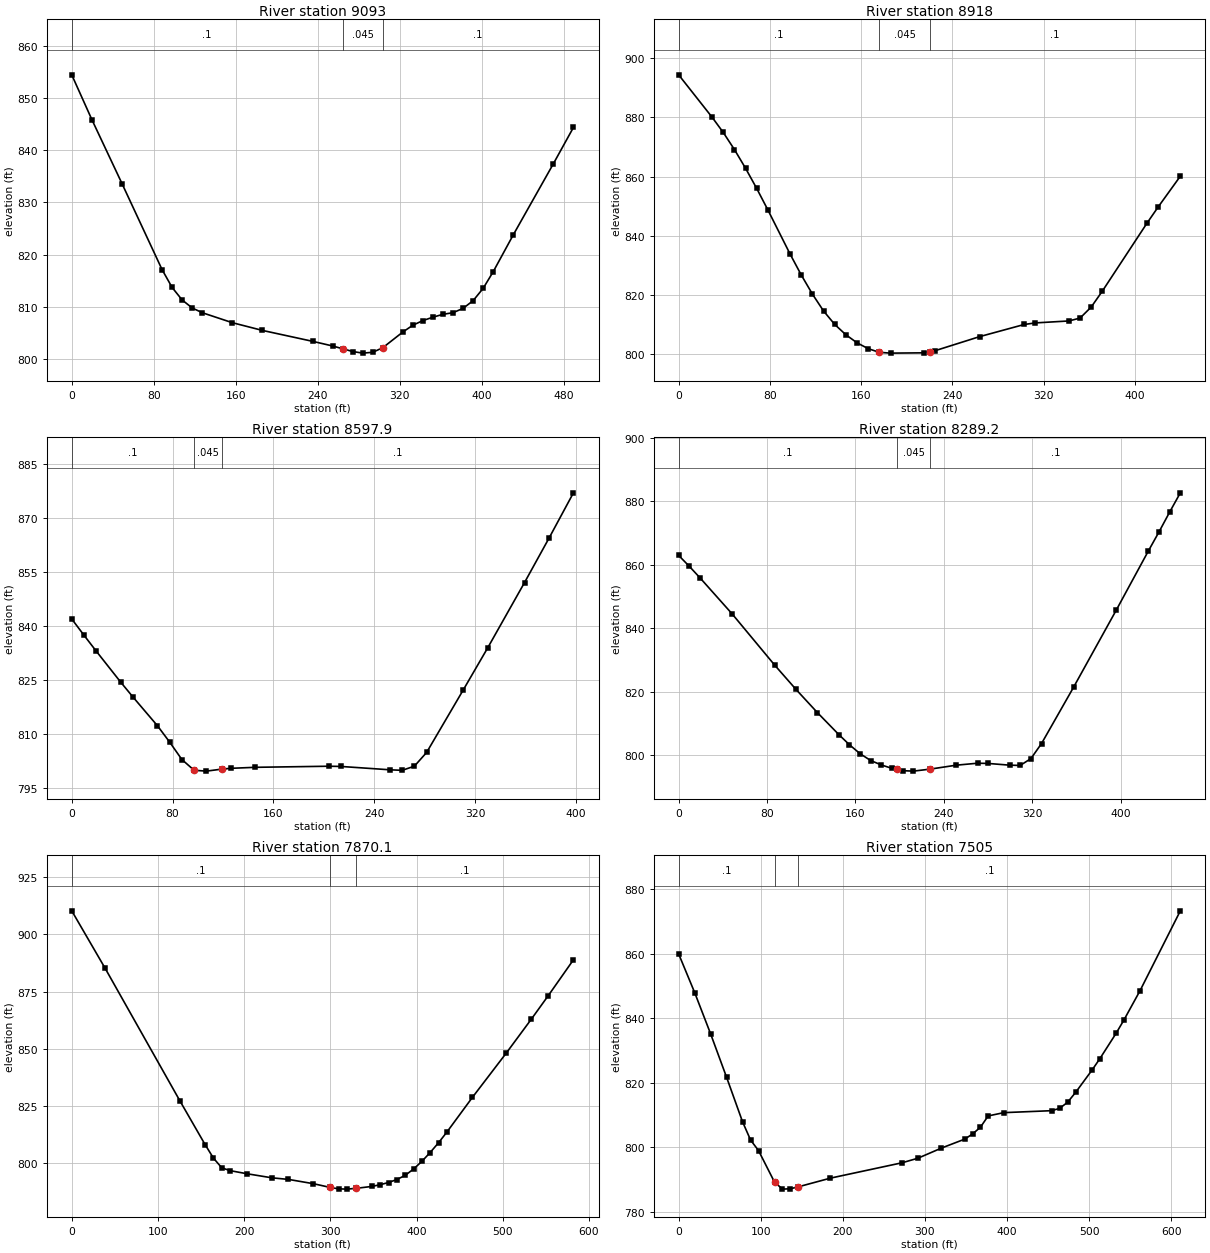
Type RM Length L Ch R = 1 ,9093    ,200.2,174.9,149.8
XS GIS Cut Line= 2
     1864811.724      487083.145     1865247.141      487306.756
#Sta/Elev= 30
       0  854.44    19.6  845.88      49  833.63    88.1  817.16    97.9  813.74
   107.7  811.34   117.5  809.81   127.3   808.9   156.6  806.99     186  805.51
     235  803.42   254.5  802.53   264.3     802   274.1  801.47   283.9  801.16
   293.7  801.32   303.5   802.2   323.1  805.21   332.8   806.5   342.6  807.39
   352.4  808.04   362.2  808.59     372   808.9   381.8  809.73   391.6   811.2
   401.4  813.56   411.2  816.74   430.7  823.77   469.9  837.41   489.5  844.37
#Mann= 3 , 0 , 0
       0      .1       0   264.3    .045       0   303.5      .1       0
Bank Sta=264.3,303.5
XS Rating Curve= 0 ,0
Exp/Cntr=0.3,0.1

Type RM Length L Ch R = 1 ,8918    ,321.8,320.1,318.1
XS GIS Cut Line= 2
     1864864.976      487456.113     1865276.643      487301.529
#Sta/Elev= 30
       0  894.41    29.3  880.08    39.1  874.92    48.9  869.14    58.6  862.84
    68.4     856    78.2  848.73    97.7  833.78   107.5   826.7   117.3  820.23
     127  814.56   136.8     810   146.6   806.5   156.4  803.78   166.1  801.81
   175.9  800.57   185.7   800.3     215   800.4   219.9  800.76   224.8  801.13
   263.8  805.88   302.9  809.99   312.7  810.52     342  811.18   351.8  812.15
   361.6  815.89   371.3  821.24   410.4  844.21   420.2  849.69   439.7  860.13
#Mann= 3 , 0 , 0
       0      .1       0   175.9    .045       0   219.9      .1       0
Bank Sta=175.9,219.9
XS Rating Curve= 0 ,0
Exp/Cntr=0.3,0.1

Type RM Length L Ch R = 1 ,8597.9  ,312.5,308.8,305
XS GIS Cut Line= 2
      1865050.06      487731.779     1865414.047      487570.435
#Sta/Elev= 24
       0  841.82     9.7  837.31    19.4   832.9    38.8  824.29    48.6  820.13
      68  812.16    77.7  807.61    87.4  802.77    97.1  799.79   106.8  799.55
   119.6  800.13   126.2  800.33   145.7  800.61   203.9  800.91   213.6  800.85
   252.5  799.92   262.2  799.77   271.9  800.93   281.6  804.74   310.8  822.19
   330.2  833.88   359.3  851.95   378.7  864.27   398.1  876.87
#Mann= 3 , 0 , 0
       0      .1       0    97.1    .045       0   119.6      .1       0
Bank Sta=97.1,119.6
XS Rating Curve= 0 ,0
Exp/Cntr=0.3,0.1

Type RM Length L Ch R = 1 ,8289.2  ,429.6,419.1,408.2
XS GIS Cut Line= 2
     1865146.994      488047.007     1865533.244       487808.64
#Sta/Elev= 30
       0  862.93     9.7  859.48    19.3  855.88    48.3  844.55    86.9  828.37
   106.2  820.71   125.5  813.43   144.9   806.5   154.5   803.3   164.2  800.46
   173.8  798.31   183.5  796.91   193.1  795.84   197.7   795.5   202.8  795.12
   212.4  794.98   227.7  795.62   251.1  796.85   270.4  797.47     280   797.4
   299.4  796.86     309  796.77   318.7  798.92   328.3  803.66   357.3   821.4
   395.9  845.68   424.9  864.29   434.6  870.34   444.2  876.56   453.9  882.65
#Mann= 3 , 0 , 0
       0      .1       0   197.7    .045       0   227.7      .1       0
Bank Sta=197.7,227.7
XS Rating Curve= 0 ,0
Exp/Cntr=0.3,0.1

Type RM Length L Ch R = 1 ,7870.1  ,360.7,365,369
XS GIS Cut Line= 3
     1865459.392      488442.139     1865718.492      488117.067
     1865757.029      487955.393
#Sta/Elev= 30
       0  910.35    38.7  885.21   125.7     827   154.7     808   164.4  802.08
     174  797.86   183.7  796.62     203  795.28     232  793.49   251.4  792.78
   280.4   790.9   299.8  789.27   309.4  788.66     319  788.53   329.8  788.87
     348  789.71   357.7  790.46   367.4  791.43     377  792.72   386.7  794.54
   396.4  797.31     406  800.64   415.7  804.55   425.5  808.86   435.2  813.55
   464.6  828.64   503.7  847.94     533   862.9   552.6  873.17   581.9  888.92
#Mann= 3 , 0 , 0
       0      .1       0   299.8    .045       0   329.8      .1       0
Bank Sta=299.8,329.8
XS Rating Curve= 0 ,0
Exp/Cntr=0.3,0.1

Type RM Length L Ch R = 1 ,7505    ,289.6,310.1,330.5
XS GIS Cut Line= 4
     1865832.348      488529.424     1866036.708      488334.875
     1866115.305      488227.698     1866295.389      488149.979
#Sta/Elev= 30
       0  860.01    19.5  848.02    38.9  835.23    58.4  821.73    77.8  807.95
    87.6  802.27    97.3  798.99   116.8   789.2   126.5  787.02   136.2  787.14
   145.7  787.73   184.9  790.43   272.4  795.21   291.6  796.62   320.1  799.75
   348.6  802.54   358.1  804.14   367.6  806.21   377.1  809.73   396.1  810.75
   454.3  811.36   464.1  812.07   473.9  813.98   483.7  817.06   503.3  823.84
   513.1  827.47   532.8  835.31   542.6  839.55   562.2  848.64   611.2  873.37
#Mann= 3 , 0 , 0
       0      .1       0   116.8    .045       0   145.7      .1       0
Bank Sta=116.8,145.7
XS Rating Curve= 0 ,0
Exp/Cntr=0.3,0.1

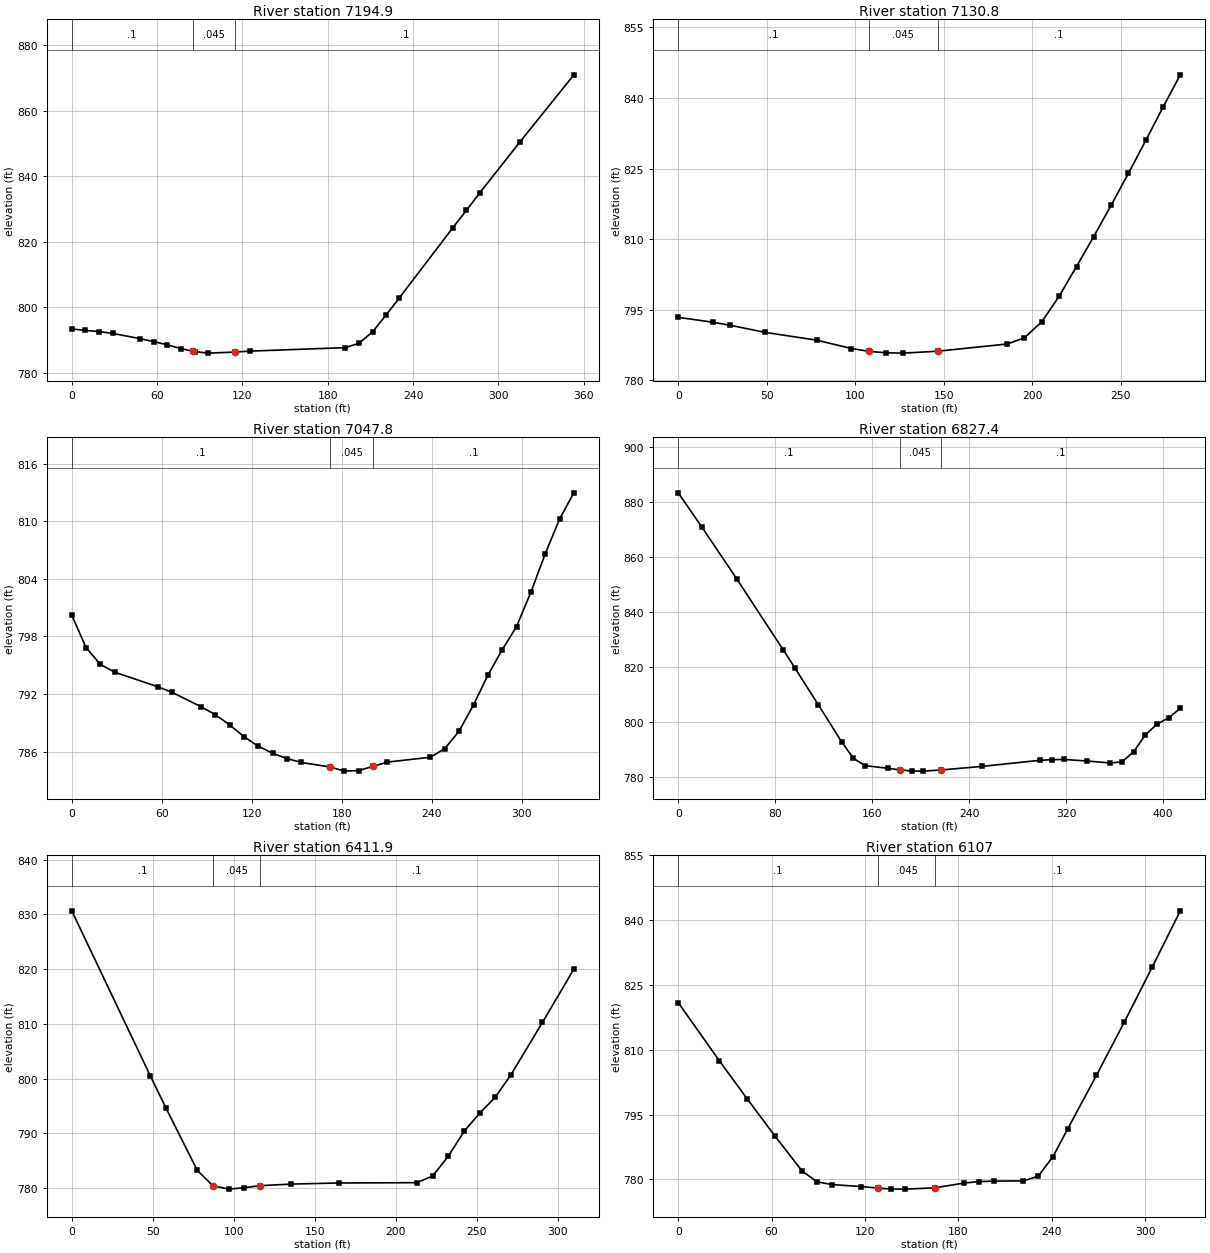
Type RM Length L Ch R = 1 ,7194.9  ,48.2,64.1,79.2
XS GIS Cut Line= 3
     1865945.893      488727.891     1866156.658       488710.41
     1866288.866      488761.174
#Sta/Elev= 23
       0  793.42     9.6  792.96    19.2  792.61    28.8  792.05    48.1  790.45
    57.7  789.53    67.3  788.57    76.9  787.41      85  786.63    86.5  786.48
    96.1  786.04     115  786.37     125  786.65   192.3  787.71   201.9  789.04
   211.5   792.5   220.9  797.58   230.4  802.91   268.1  824.34   277.6  829.62
     287  834.95   315.3  850.51   353.1  870.92
#Mann= 3 , 0 , 0
       0      .1       0      85    .045       0     115      .1       0
Bank Sta=85,115
XS Rating Curve= 0 ,0
Exp/Cntr=0.3,0.1

Type RM Length L Ch R = 1 ,7130.8  ,83.2,83,82.5
XS GIS Cut Line= 2
     1865947.749      488739.006     1866210.022      488846.701
#Sta/Elev= 21
       0  793.39    19.6  792.34    29.3   791.7    48.9   790.2    78.2  788.53
    97.8  786.76   107.5  786.17   117.3  785.85   127.1  785.78   146.6  786.19
   185.8  787.72   195.5  789.04   205.3  792.46   215.1  797.88   224.9  804.18
   234.6  810.55   244.4  817.18   254.2  823.98     264  830.98   273.8   838.1
   283.5  844.92
#Mann= 3 , 0 , 0
       0      .1       0   107.5    .045       0   146.6      .1       0
Bank Sta=107.5,146.6
XS Rating Curve= 0 ,0
Exp/Cntr=0.3,0.1

Type RM Length L Ch R = 1 ,7047.8  ,252.2,220.4,188.7
XS GIS Cut Line= 2
     1865893.824      488797.433     1866203.564      488924.617
#Sta/Elev= 30
       0  800.21     9.6   796.8    19.1  795.08    28.7  794.26    57.4  792.75
      67  792.16    86.1  790.68    95.7  789.84   105.2  788.79   114.8  787.55
   124.4  786.55   133.9  785.82   143.5  785.27   153.1  784.86   172.2  784.39
   181.8  783.96   191.3  784.02   200.9  784.46   210.5   784.9   239.2  785.41
   248.7   786.3   258.3  788.14   267.9  790.86   277.4  793.93     287   796.6
   296.6  799.02   306.1  802.58   315.7  806.59   325.3  810.23   334.8  812.95
#Mann= 3 , 0 , 0
       0      .1       0   172.2    .045       0   200.9      .1       0
Bank Sta=172.2,200.9
XS Rating Curve= 0 ,0
Exp/Cntr=0.3,0.1

Type RM Length L Ch R = 1 ,6827.4  ,443.8,415.6,387.5
XS GIS Cut Line= 2
     1865886.602      489202.141      1866222.54      488959.953
#Sta/Elev= 26
       0  883.39    19.3  871.06    48.2  852.11    86.7  826.17    96.3  819.59
   115.6   806.2   134.8  792.75   144.5  786.77   154.1  784.09   173.4  783.11
     183  782.54   192.6  782.15   202.2   782.1   216.5  782.51   250.4  783.81
   298.6  786.05   308.2  786.27   317.8  786.35   337.1  785.79   356.4  785.06
     366  785.47   375.6  789.14   385.2  795.26   394.9  799.19   404.5  801.53
   414.1  804.94
#Mann= 3 , 0 , 0
       0      .1       0     183    .045       0   216.5      .1       0
Bank Sta=183,216.5
XS Rating Curve= 0 ,0
Exp/Cntr=0.3,0.1

Type RM Length L Ch R = 1 ,6411.9  ,300.8,304.9,308.8
XS GIS Cut Line= 2
     1866398.688      489311.438     1866401.203       489001.48
#Sta/Elev= 19
       0  830.65    48.4  800.57    58.1  794.67    77.5  783.24    87.2  780.43
    96.9  779.82   106.6  780.08   116.2  780.45   135.6  780.74   164.7  780.94
   213.1     781   222.8  782.22   232.5  785.82   242.2  790.37   251.8  793.67
   261.5  796.61   271.2  800.73   290.6  810.26     310     820
#Mann= 3 , 0 , 0
       0      .1       0    87.2    .045       0   116.2      .1       0
Bank Sta=87.2,116.2
XS Rating Curve= 0 ,0
Exp/Cntr=0.3,0.1

Type RM Length L Ch R = 1 ,6107    ,103.5,97.4,90.5
XS GIS Cut Line= 4
     1866668.193      489336.689     1866694.859      489261.689
     1866720.137      489083.356     1866737.081        489022.8
#Sta/Elev= 23
       0  820.91    26.5  807.41    44.2  798.69    61.9  790.15    79.6  781.93
    89.1  779.44    98.6   778.8   117.5  778.34   128.5  777.97   136.5  777.76
     146  777.74   164.9  778.04   183.9  779.16   193.4  779.48   202.8   779.6
   221.8  779.64   231.3  780.74   240.8  785.27   250.2  791.66   268.7  804.07
   286.7  816.46   304.6  829.16   322.6  842.16
#Mann= 3 , 0 , 0
       0      .1       0   128.5    .045       0   164.9      .1       0
Bank Sta=128.5,164.9
XS Rating Curve= 0 ,0
Exp/Cntr=0.3,0.1

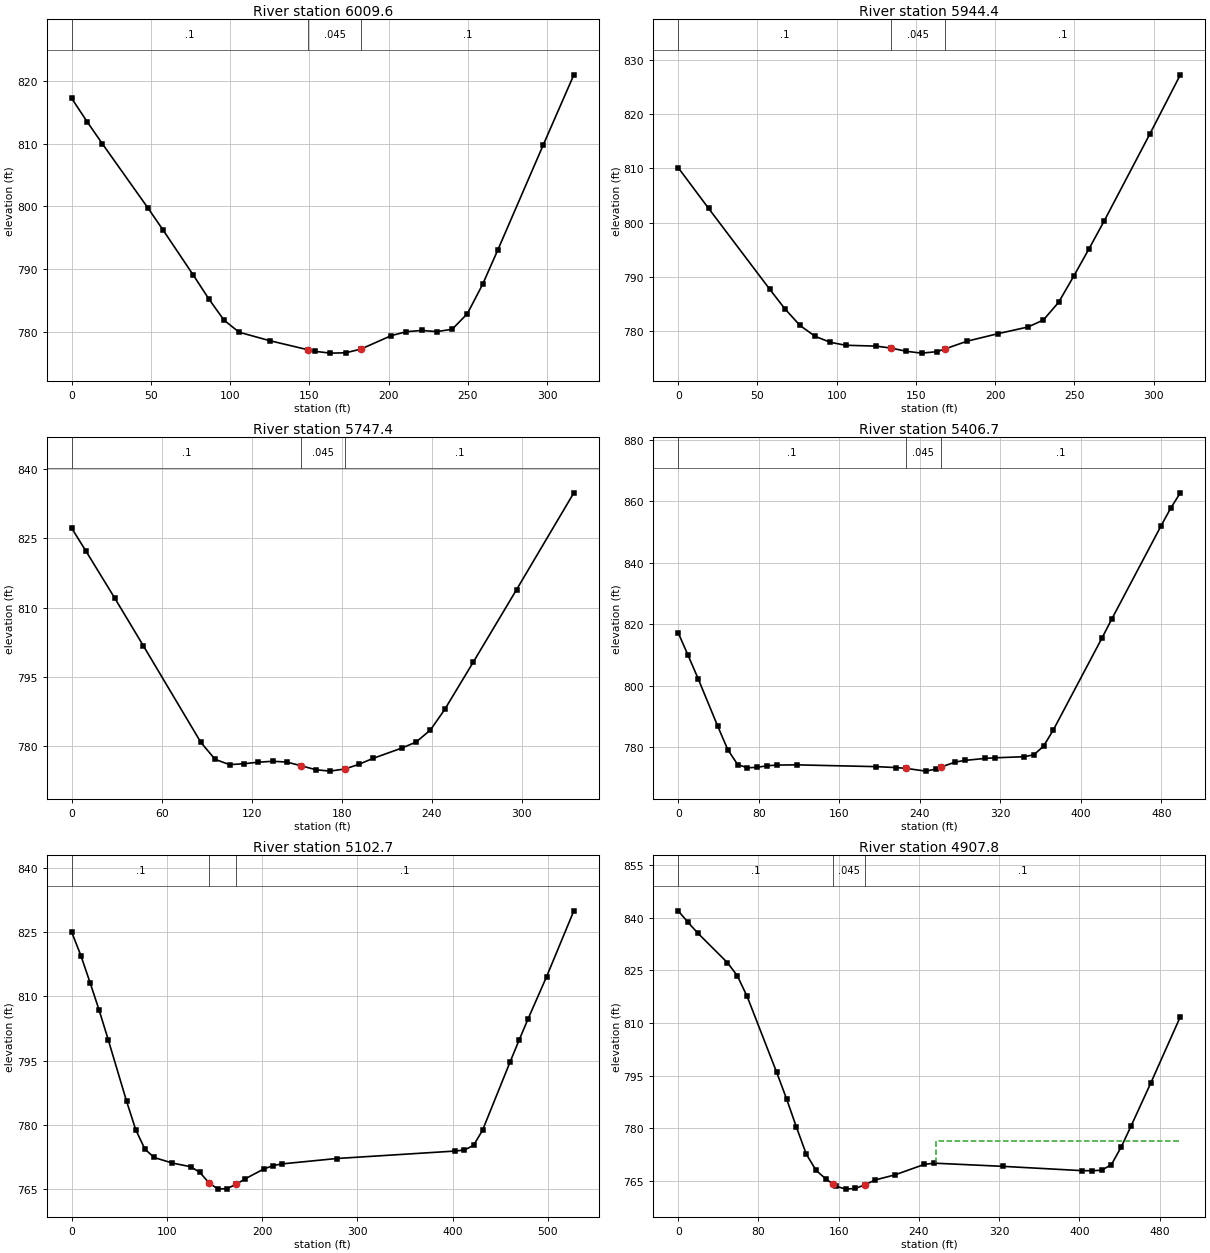
Type RM Length L Ch R = 1 ,6009.6  ,65.9,65.3,65.6
XS GIS Cut Line= 2
     1866803.841       489388.11     1866789.905      489071.658
#Sta/Elev= 25
       0  817.19     9.6  813.52    19.2  810.01      48  799.76    57.6  796.23
    76.8     789    86.4  785.28      96  781.88   105.6  779.94   124.8   778.6
   149.3  777.13   153.6  776.89   163.2  776.61   172.8  776.66   182.4  777.25
   201.6   779.4   211.2  780.03   220.8  780.22   230.4  780.04     240  780.41
   249.6  782.89   259.2  787.55   268.8  793.04   297.6  809.85   316.8  820.96
#Mann= 3 , 0 , 0
       0      .1       0   149.3    .045       0   182.4      .1       0
Bank Sta=149.3,182.4
XS Rating Curve= 0 ,0
Exp/Cntr=0.3,0.1

Type RM Length L Ch R = 1 ,5944.4  ,179.1,196.9,214.5
XS GIS Cut Line= 2
     1866863.563      489402.693     1866849.627      489086.241
#Sta/Elev= 24
       0  810.14    19.2  802.64    57.6  787.82    67.2   784.2    76.8  781.11
    86.4   779.1      96     778   105.6  777.46   124.8   777.3   134.4  776.94
     144  776.34   153.6  776.01   163.2  776.28   168.6  776.81   182.4  778.22
   201.6  779.58   220.8  780.83   230.4  782.11     240  785.36   249.6   790.2
   259.2  795.22   268.8  800.36   297.6  816.36   316.8  827.24
#Mann= 3 , 0 , 0
       0      .1       0   134.4    .045       0   168.6      .1       0
Bank Sta=134.4,168.6
XS Rating Curve= 0 ,0
Exp/Cntr=0.3,0.1

Type RM Length L Ch R = 1 ,5747.4  ,330.9,340.7,350.2
XS GIS Cut Line= 2
     1866943.901      489496.773      1867105.92      489203.888
#Sta/Elev= 24
       0  827.18     9.6  822.16    28.7  812.02    47.8  801.67    86.1  780.75
    95.6  777.08   105.2  775.95   114.8  776.14   124.3  776.48   133.9  776.67
   143.4  776.51     153  775.69   162.6  774.85   172.1  774.54   182.1  775.01
   191.3     776   200.8   777.3     220  779.54   229.5  780.83   239.1  783.46
   248.6   787.9   267.8  798.25   296.5  813.88   334.7  834.87
#Mann= 3 , 0 , 0
       0      .1       0     153    .045       0   182.1      .1       0
Bank Sta=153,182.1
XS Rating Curve= 0 ,0
Exp/Cntr=0.3,0.1

Type RM Length L Ch R = 1 ,5406.7  ,271.1,304,336.9
XS GIS Cut Line= 3
     1867157.368      489637.653     1867381.118      489430.778
     1867391.535      489237.028
#Sta/Elev= 30
       0  817.23     9.8  809.92    19.7  802.38    39.3  786.81    49.2  779.24
      59  774.39    68.8  773.32    78.6   773.5    88.5  773.99    98.3  774.21
     118  774.28   196.6   773.7   216.3   773.4   226.1  773.15   245.8  772.24
   255.6  772.88     261  773.56   275.2  775.19   285.1  775.74   304.7  776.37
   314.4  776.57   343.5  776.93   353.2  777.54   362.9  780.35   372.6  785.62
   421.2   815.7   430.8  821.79   479.4   851.9   489.1  857.73   498.8  862.81
#Mann= 3 , 0 , 0
       0      .1       0   226.1    .045       0     261      .1       0
Bank Sta=226.1,261
XS Rating Curve= 0 ,0
Exp/Cntr=0.3,0.1

Type RM Length L Ch R = 1 ,5102.7  ,177.5,194.9,212.2
XS GIS Cut Line= 3
     1867186.444      489692.615      1867467.09      489791.125
     1867693.584      489829.638
#Sta/Elev= 30
       0  824.98     9.6  819.53    19.2  813.22    28.8  806.74    38.4  799.77
    57.6  785.44    67.2  778.79    76.8  774.28    86.4  772.32   105.5  771.03
   124.7  770.16   134.3  768.88   143.9  766.44   153.5  764.92   163.1  765.06
   172.7  766.06   182.3  767.36   201.5  769.61   211.1  770.41   220.7  770.82
   278.2  772.08   402.7  773.83   412.3  774.07   421.9  775.15   431.4  778.73
   460.2  794.64   469.7  799.77   479.3  804.82   498.5  814.57   527.2  830.01
#Mann= 3 , 0 , 0
       0      .1       0   143.9    .045       0   172.7      .1       0
Bank Sta=143.9,172.7
XS Rating Curve= 0 ,0
Exp/Cntr=0.3,0.1

Type RM Length L Ch R = 1 ,4907.8  ,369.4,356.9,344
XS GIS Cut Line= 2
     1867115.758      489766.462     1867421.604       490162.64
#Sta/Elev= 30
       0  841.99     9.8  838.68    19.6  835.61    49.1   827.2    58.9  823.48
    68.7  817.57    98.1  795.98     108  788.38   117.8  780.35   127.6  772.67
   137.4     768   147.2  765.56   154.6  764.03     157  763.54   166.8  762.66
   176.6  762.85   186.5  763.95   196.3  765.28   215.9  766.71   245.3  769.71
   255.2  770.06   323.8  769.15   402.4  767.93   412.2   767.9     422  768.05
   431.8  769.63   441.6  774.68   451.4  780.65   471.1  792.93   500.5  811.79
#Mann= 3 , 0 , 0
       0      .1       0   154.6    .045       0   186.5      .1       0
#XS Ineff= 2 , 0
                          256.59           776.3
Permanent Ineff=
       F       F
Bank Sta=154.6,186.5
XS Rating Curve= 0 ,0
Exp/Cntr=0.3,0.1

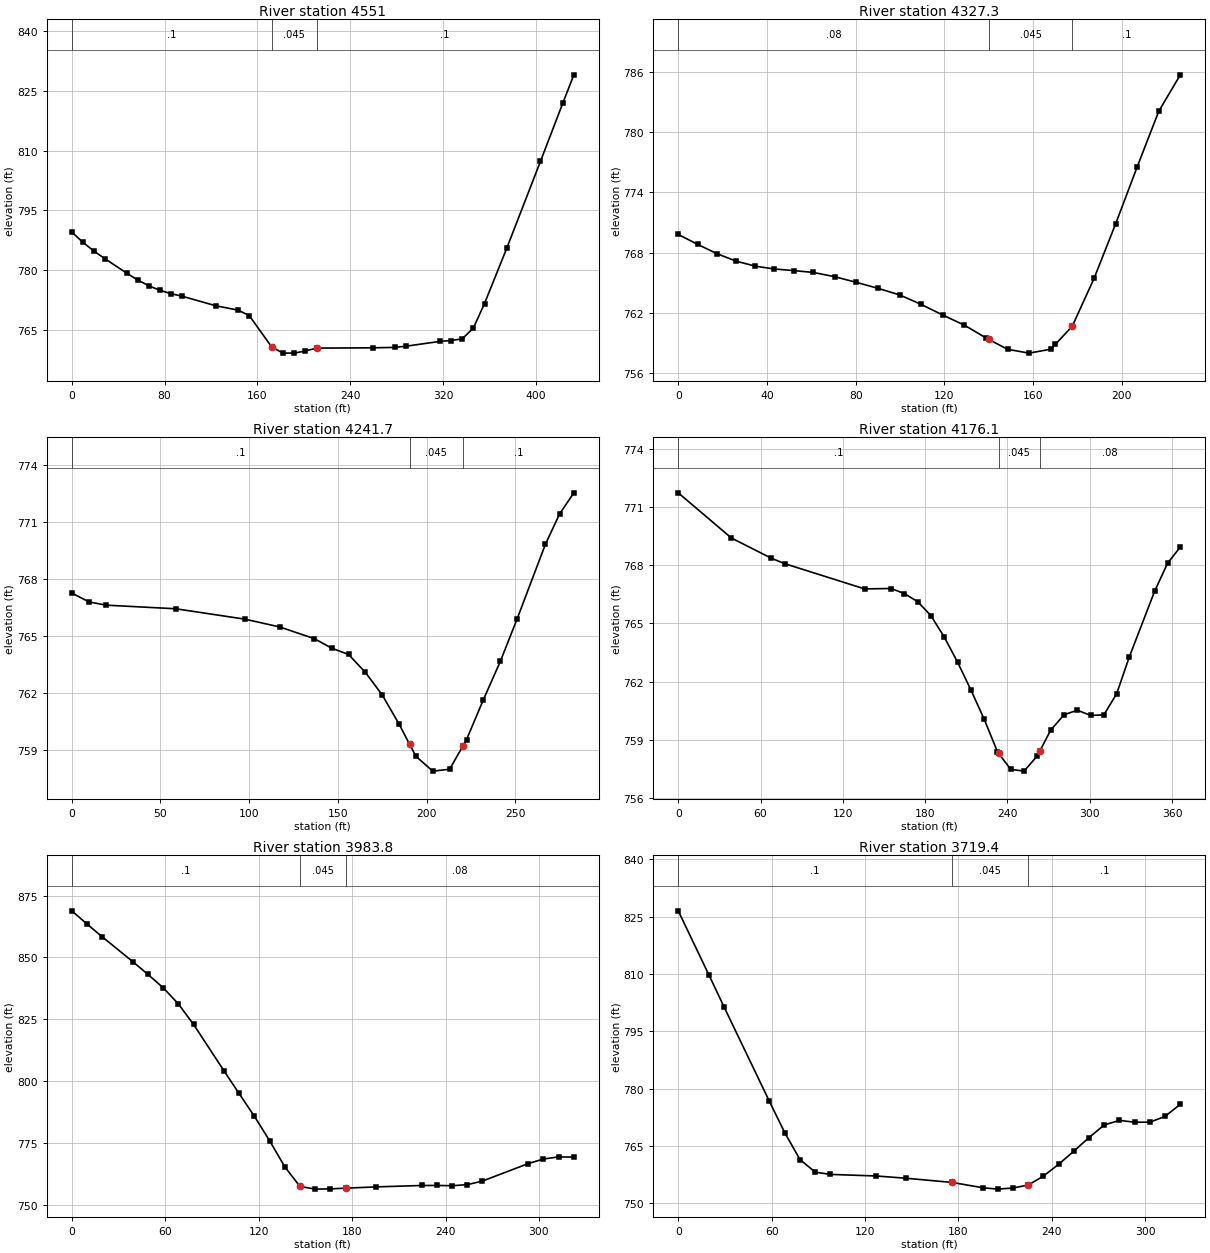
Type RM Length L Ch R = 1 ,4551    ,208.6,223.6,238.5
XS GIS Cut Line= 4
     1866846.882      490012.676      1866887.16      490098.787
     1867048.965      490185.593     1867119.799      490322.398
#Sta/Elev= 30
       0  789.57     9.5     787      19  784.81    28.5  782.88    47.5  779.21
      57  777.49    66.6  776.05      76  774.93    85.6  774.09    95.1  773.45
   124.1  771.06   143.4  769.96     153  768.58   172.4  760.67     182  759.19
   191.7  759.17   201.4  759.72     211  760.43   259.4   760.5   278.7  760.61
   288.3  760.92   317.2  762.11   326.8  762.33   336.5  762.75   346.1  765.46
   355.7  771.61     375  785.59   403.9  807.28   423.1  821.86   432.7  829.02
#Mann= 3 , 0 , 0
       0      .1       0   172.4    .045       0     211      .1       0
Bank Sta=172.4,211
XS Rating Curve= 0 ,0
Exp/Cntr=0.3,0.1

Type RM Length L Ch R = 1 ,4327.3  ,89.5,85.6,81.6
XS GIS Cut Line= 3
     1866778.184      490174.945     1866779.693       490235.75
     1866870.684      490374.111
#Sta/Elev= 27
       0   769.8     8.7  768.82    17.4  767.89    26.1  767.14    34.8  766.64
    43.4  766.36    52.1   766.2    60.8  766.02    70.6  765.59    80.3  765.03
      90  764.44    99.8  763.78   109.5  762.84   119.3  761.77     129  760.77
   138.8  759.49     140  759.35   148.5  758.36   158.2  757.98     168  758.37
     170  758.84   177.7  760.67   187.5  765.42   197.2  770.84   206.9   776.5
   216.7  782.08   226.4   785.7
#Mann= 3 , 0 , 0
       0     .08       0     140    .045       0   177.7      .1       0
Bank Sta=140,177.7
XS Rating Curve= 0 ,0
Exp/Cntr=0.3,0.1

Type RM Length L Ch R = 1 ,4241.7  ,65.7,65.7,65.7
XS GIS Cut Line= 4
     1866709.286      490164.736     1866717.955         490311.
     1866786.257       490390.13     1866816.439       490400.57
#Sta/Elev= 24
       0  767.26     9.8  766.79    19.5  766.62    58.6  766.43    97.7  765.88
   117.2  765.47   136.8  764.85   146.5  764.35     156  764.02   165.5  763.07
     175  761.88   184.5  760.34   190.4  759.28     194  758.64   203.5  757.86
     213  757.96   220.4  759.18   222.5  759.52     232  761.63   241.6  763.66
     251  765.89     267  769.84     275  771.44     283  772.55
#Mann= 3 , 0 , 0
       0      .1       0   190.4    .045       0   220.4      .1       0
Bank Sta=190.4,220.4
XS Rating Curve= 0 ,0
Exp/Cntr=0.3,0.1

Type RM Length L Ch R = 1 ,4176.1  ,238,192.3,146.5
XS GIS Cut Line= 3
      1866540.12       490205.57     1866743.349      490440.066
     1866796.943      490455.057
#Sta/Elev= 29
       0  771.73    38.8   769.4    67.9  768.36    77.6  768.08   135.8  766.78
   155.2   766.8   164.8  766.54   174.6  766.12   184.2   765.4   193.9   764.3
   203.6  763.01   213.3  761.58     223  760.07   232.7  758.39   233.5  758.31
   242.4  757.48   252.1  757.39   261.8  758.18   263.5  758.41   271.5   759.5
   281.2  760.29   290.9  760.53   300.6  760.26   310.3  760.29   319.6  761.38
   328.9  763.29   347.4  766.68   356.7   768.1     366  768.94
#Mann= 3 , 0 , 0
       0      .1       0   233.5    .045       0   263.5     .08       0
Bank Sta=233.5,263.5
XS Rating Curve= 0 ,0
Exp/Cntr=0.3,0.1

Type RM Length L Ch R = 1 ,3983.8  ,273.4,264.4,254.6
XS GIS Cut Line= 2
     1866553.372      490649.099     1866809.402      490453.238
#Sta/Elev= 27
       0  868.82     9.8  863.48    19.5  858.35    39.1  848.32    48.8  843.19
    58.6  837.81    68.4  831.25    78.2  822.93    97.7  804.22   107.4  795.03
   117.2  785.88     127  775.99   136.8  765.38   146.5  757.49   156.3  756.38
   166.1  756.49   175.8  756.77   195.4  757.28   224.7  757.85   234.4  757.86
   244.2  757.76     254  758.18   263.7  759.64     293  766.67   302.8  768.54
   312.6   769.4   322.4  769.32
#Mann= 3 , 0 , 0
       0      .1       0   146.5    .045       0   175.8     .08       0
Bank Sta=146.5,175.8
XS Rating Curve= 0 ,0
Exp/Cntr=0.3,0.1

Type RM Length L Ch R = 1 ,3719.4  ,353.4,356.6,359.3
XS GIS Cut Line= 2
     1866818.958      490764.586     1867003.958      490500.419
#Sta/Elev= 25
       0  826.49    19.6  809.81    29.3  801.47    58.6  776.63    68.4  768.49
    78.2  761.44      88  758.15    97.7  757.56     127  757.15   146.6  756.55
   175.9  755.46   195.5  754.08   205.2  753.71     215     754   224.8  754.78
   234.6  757.13   244.3  760.19   254.1  763.64   263.9  767.21   273.6  770.48
   283.4  771.69   293.2  771.21     303  771.22   312.7  772.73   322.5  775.89
#Mann= 3 , 0 , 0
       0      .1       0   175.9    .045       0   224.8      .1       0
Bank Sta=175.9,224.8
XS Rating Curve= 0 ,0
Exp/Cntr=0.3,0.1