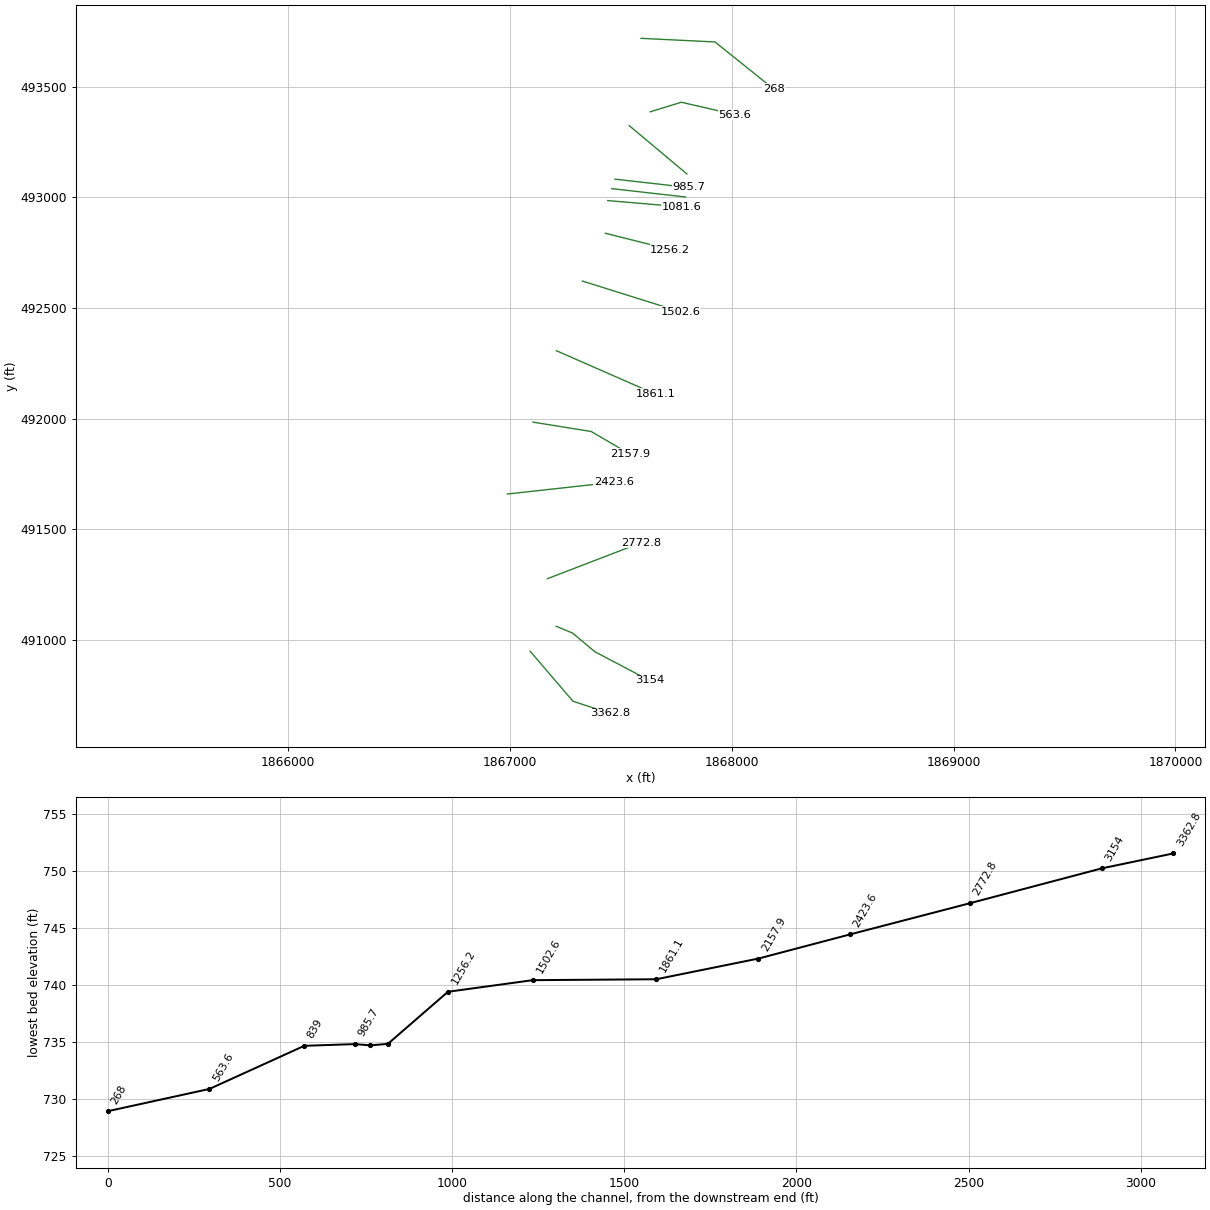
HEC-RAS study MORRISFK.prj: MORRISFK

--- MORRISFK.g01 (geometry) --- (continued)

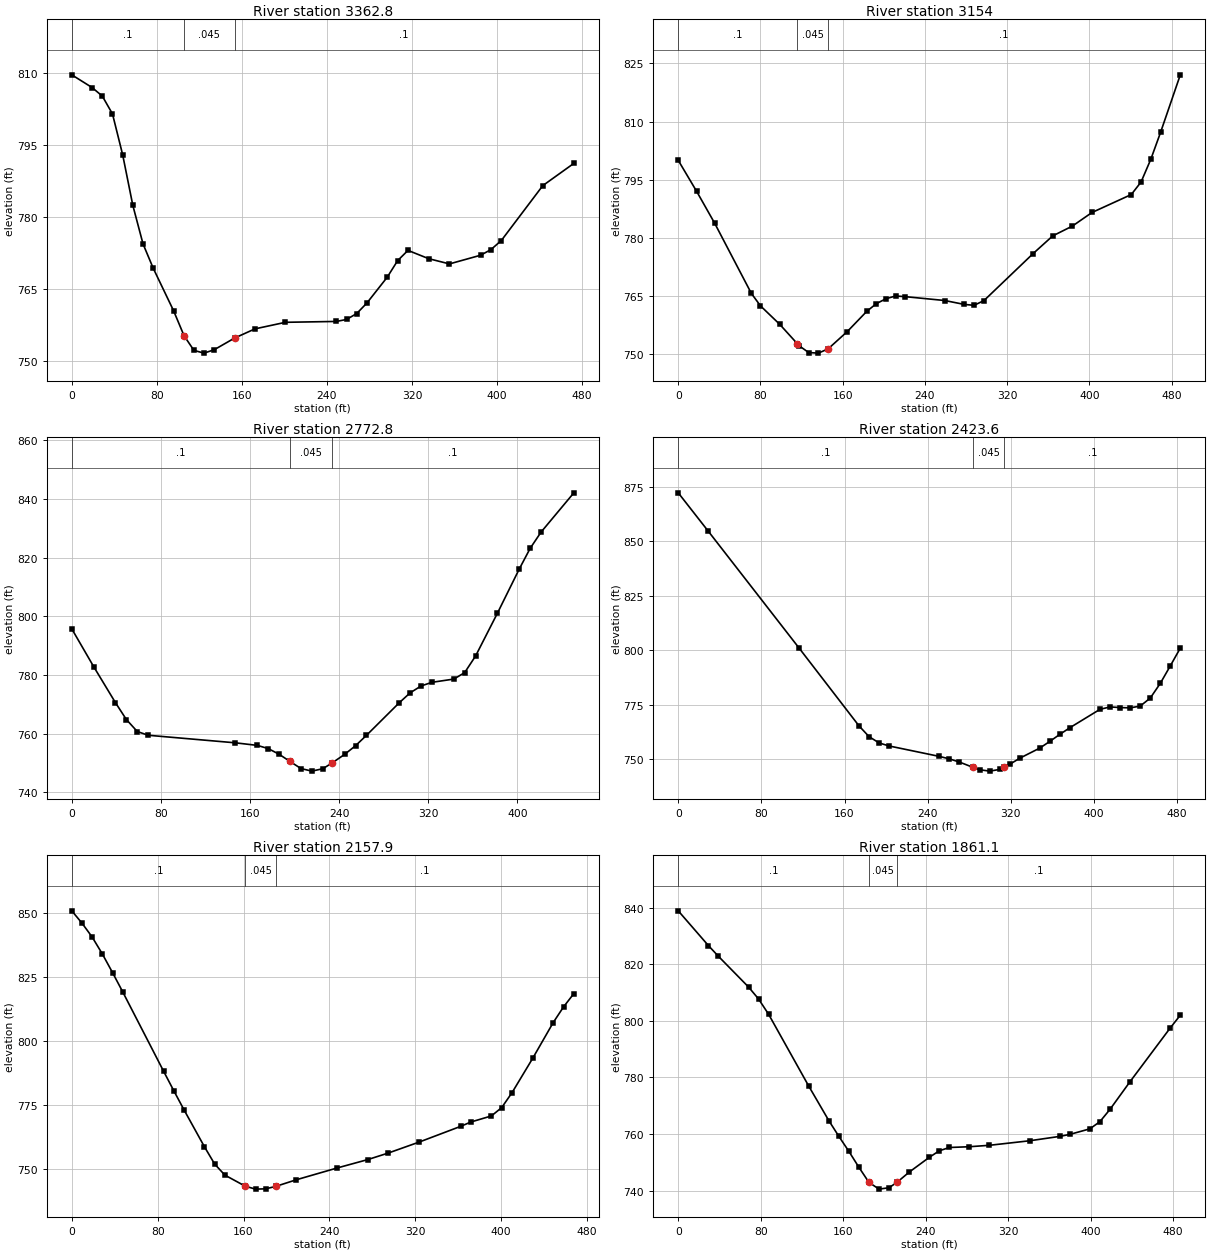
Type RM Length L Ch R = 1 ,3362.8  ,203.7,208.8,213.7
XS GIS Cut Line= 3
     1867091.684      490949.832     1867284.462      490724.277
     1867451.129      490669.277
#Sta/Elev= 30
       0  809.61    19.1  806.96    28.7  805.18    38.3  801.45    47.9   792.9
    57.4   782.4      67  774.35    76.6  769.27    95.7  760.43   105.6  755.19
   114.9  752.13   124.4  751.56     134  752.27   153.1   754.7   172.3  756.62
     201  757.99   248.9  758.17   258.4  758.58     268  759.82   277.6  762.02
   296.7   767.4   306.5  770.86   316.2  772.99   335.7  771.26   355.2  770.17
   384.5  771.98   394.2  773.15     404  775.05     443   786.5   472.2  791.14
#Mann= 3 , 0 , 0
       0      .1       0   105.6    .045       0   153.1      .1       0
Bank Sta=105.6,153.1
XS Rating Curve= 0 ,0
Exp/Cntr=0.3,0.1

Type RM Length L Ch R = 1 ,3154    ,349,381.2,413.2
XS GIS Cut Line= 4
     1867209.101      491062.671     1867282.899      491031.907
     1867383.733      490947.506     1867628.733      490818.339
#Sta/Elev= 30
       0     800    17.8  792.04    35.5  783.74    71.1  765.67      80  762.44
    98.7  757.68   115.8  752.68   117.5  752.16   126.9  750.39   136.3  750.24
   145.8  751.34   164.5  755.82   183.3     761   192.7  763.01   202.1  764.28
   211.4  764.99     221  764.81   259.2  763.82   278.3  762.81   287.8  762.58
   297.4   763.8   345.2  775.93   364.3   780.5   383.4  783.03   402.5  786.54
   440.7  791.17   450.2   794.4   459.8  800.34   469.3   807.3   488.4  822.07
#Mann= 3 , 0 , 0
       0      .1       0   115.8    .045       0   145.8      .1       0
Bank Sta=115.8,145.8
XS Rating Curve= 0 ,0
Exp/Cntr=0.3,0.1

Type RM Length L Ch R = 1 ,2772.8  ,356.9,349.2,341.5
XS GIS Cut Line= 2
     1867169.852      491277.798     1867590.392      491439.661
#Sta/Elev= 30
       0  795.71    19.6  782.86    39.2  770.54      49  764.79    58.8  760.69
    68.6  759.42   146.9  756.84   166.5  755.97   176.3  754.88   186.1  752.94
   195.9  750.48   205.7  748.07   215.5  747.19   225.3  748.01   233.6  749.97
   244.9   752.9   254.7  755.87   264.5   759.4   293.9   770.5   303.7  773.89
   313.5  776.23   323.3  777.48   342.9  778.58   352.6  780.78   362.4  786.44
     382  801.04   401.6   816.1   411.4  823.16   421.2  828.71   450.6  842.09
#Mann= 3 , 0 , 0
       0      .1       0   195.9    .045       0   233.6      .1       0
Bank Sta=195.9,233.6
XS Rating Curve= 0 ,0
Exp/Cntr=0.3,0.1

Type RM Length L Ch R = 1 ,2423.6  ,273.7,265.7,257.5
XS GIS Cut Line= 2
     1866988.802      491660.032     1867469.011      491713.157
#Sta/Elev= 30
       0  872.32      29  854.62     116  801.16   173.9  765.25   183.6  760.29
   193.3  757.39   202.9     756   251.2  751.21   260.9  750.07   270.6   748.6
   283.9  746.12   289.9  745.09   299.6  744.44   309.2  745.21   313.9  746.34
   318.9  747.54   328.5  750.35   347.9  755.03   357.5  758.09   367.2  761.34
   376.8  764.38   405.8  772.83   415.5  773.94   425.2  773.65   434.8  773.51
   444.5  774.32   454.2  778.02   463.8  784.74   473.5  792.83   483.1  800.98
#Mann= 3 , 0 , 0
       0      .1       0   283.9    .045       0   313.9      .1       0
Bank Sta=283.9,313.9
XS Rating Curve= 0 ,0
Exp/Cntr=0.3,0.1

Type RM Length L Ch R = 1 ,2157.9  ,304.3,296.8,288.9
XS GIS Cut Line= 3
     1867103.993      491984.815      1867366.83      491942.431
      1867540.71      491840.697
#Sta/Elev= 30
       0  851.03     9.5  846.23      19  840.78    28.5  834.17      38  826.88
    47.5  819.34    85.6  788.32    95.1  780.71   104.6  773.26   123.6  758.86
   133.1  752.12   142.6   747.8   161.6  743.47   171.2  742.32   180.7  742.44
   190.2  743.41   209.2  745.98   247.2  750.58   275.8  753.87     295  756.44
   323.8  760.73   362.2  766.83   371.8  768.54   390.9  770.91   400.5  774.18
   410.1  779.99   429.3  793.37   448.5   807.4   458.1   813.5   467.7   818.7
#Mann= 3 , 0 , 0
       0      .1       0   161.6    .045       0   190.2      .1       0
Bank Sta=161.6,190.2
XS Rating Curve= 0 ,0
Exp/Cntr=0.3,0.1

Type RM Length L Ch R = 1 ,1861.1  ,355.2,358.5,361.8
XS GIS Cut Line= 2
     1867209.754      492307.426     1867655.587      492111.592
#Sta/Elev= 30
       0  838.96    29.2  826.69      39  822.86    68.2     812    77.9  807.78
    87.6   802.4   126.6  776.94   146.1  764.72   155.8  759.17   165.6  753.82
   175.3  748.19     185  742.88   194.8   740.5   204.5     741   212.4  742.97
     224  746.51   243.5  751.74   253.2  754.06     263  755.23   282.4   755.5
   301.9  756.01   340.9  757.61   370.1  759.16   379.8  759.86   399.3  761.83
     409  764.37   418.8  768.72   438.2   778.5   477.2  797.51     487  802.04
#Mann= 3 , 0 , 0
       0      .1       0     185    .045       0   212.4      .1       0
Bank Sta=185,212.4
XS Rating Curve= 0 ,0
Exp/Cntr=0.3,0.1

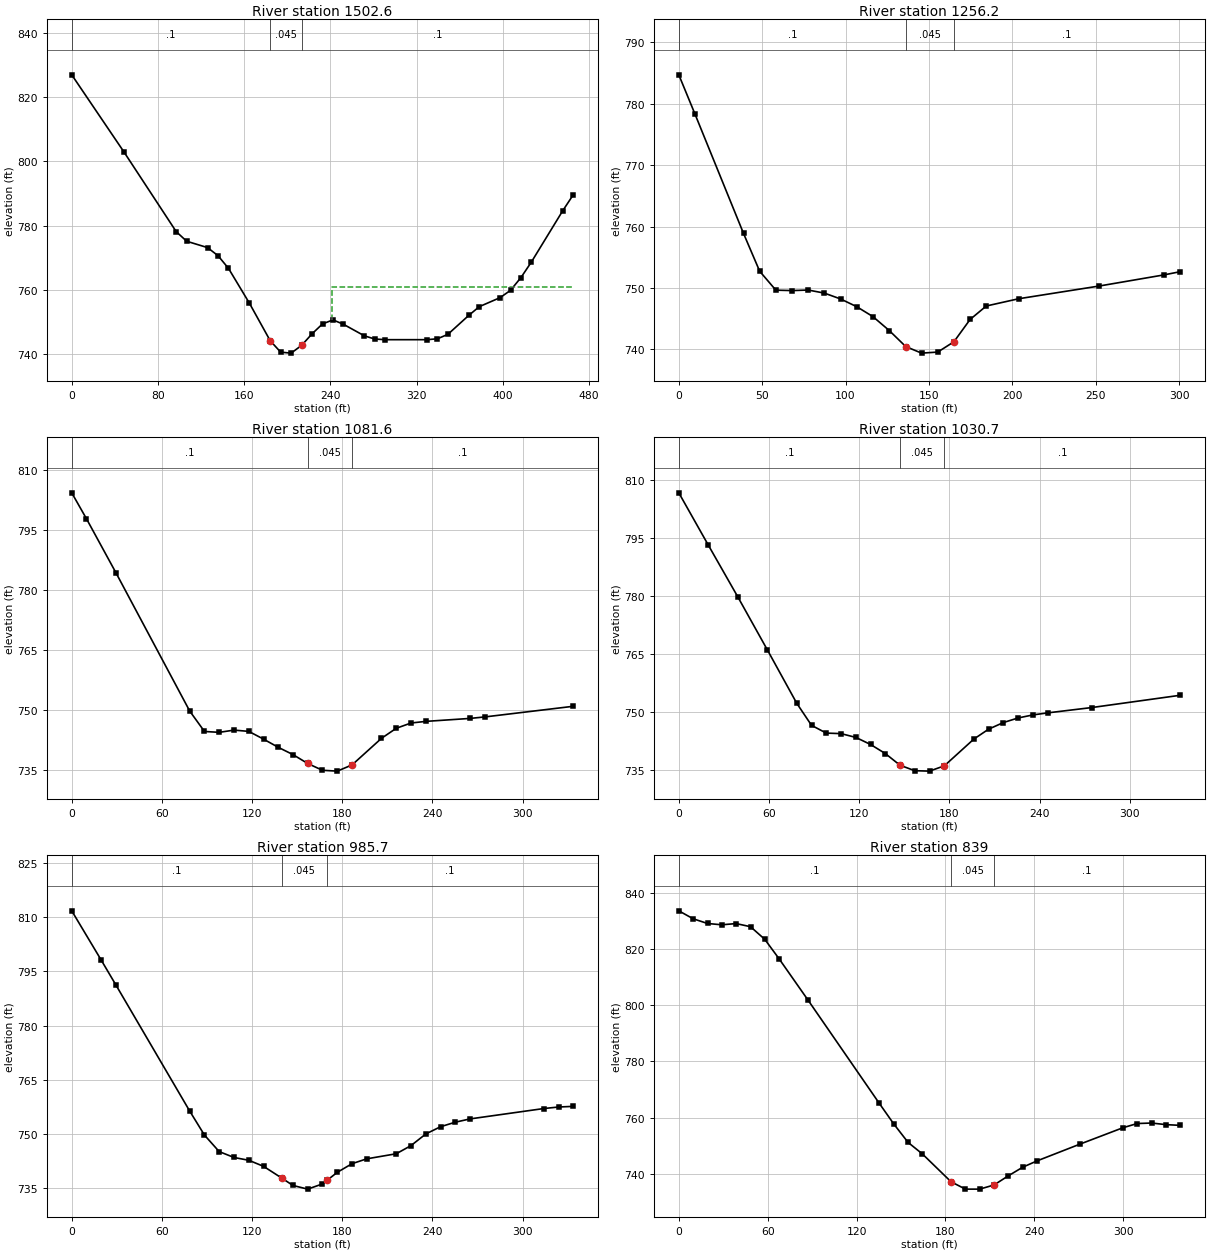
Type RM Length L Ch R = 1 ,1502.6  ,244.6,246.4,248.1
XS GIS Cut Line= 2
     1867327.115      492622.009     1867770.865      492482.426
#Sta/Elev= 30
       0  826.93    48.5  802.92    96.9  778.19   106.6   775.2     126  773.22
   135.7   770.7   145.4  766.76   164.8  755.94   184.1  744.27   193.8  740.72
   203.5  740.42   213.2  742.82   222.9  746.42   232.6   749.5   242.3  750.75
     252  749.39   271.4   745.8     281  744.81   290.7   744.6   329.5   744.6
   339.2  744.88   348.9  746.26   368.3  752.16     378  754.86   397.4  757.68
     407  759.95   416.7  763.92   426.4  768.77   455.5  784.72   465.2  789.65
#Mann= 3 , 0 , 0
       0      .1       0   184.1    .045       0   213.2      .1       0
#XS Ineff= 2 , 0
                           241.3          761.13
Permanent Ineff=
       F       F
Bank Sta=184.1,213.2
XS Rating Curve= 0 ,0
Exp/Cntr=0.3,0.1

Type RM Length L Ch R = 1 ,1256.2  ,169.5,174.5,179.2
XS GIS Cut Line= 2
     1867430.774      492837.872      1867722.44       492764.26
#Sta/Elev= 22
       0   784.7     9.7  778.31    38.8  758.89    48.5  752.73    58.2  749.65
    67.9  749.58    77.6  749.67    87.3  749.17      97  748.22   106.7  746.96
   116.4  745.35   126.2  743.08   136.1  740.47   145.6   739.4   155.3  739.57
     165  741.25   174.7  744.88   184.4  747.07   203.8  748.25   252.3  750.33
   291.1  752.14   300.8  752.66
#Mann= 3 , 0 , 0
       0      .1       0   136.1    .045       0     165      .1       0
Bank Sta=136.1,165
XS Rating Curve= 0 ,0
Exp/Cntr=0.3,0.1

Type RM Length L Ch R = 1 ,1081.6  ,51.8,51,50.1
XS GIS Cut Line= 2
     1867441.269      492985.465     1867773.747      492957.043
#Sta/Elev= 22
       0  804.36     9.8  797.88    29.4  784.39    78.5  749.83    88.3  744.73
    98.1  744.51     108  745.07   117.8  744.75   127.6  742.82   137.4  740.77
   147.2  738.95     157  736.73   166.8  735.03   176.7  734.82   186.5  736.37
   206.1  743.02   215.9  745.52   225.7  746.84   235.6  747.25     265  747.99
   274.8  748.36   333.7  751.02
#Mann= 3 , 0 , 0
       0      .1       0     157    .045       0   186.5      .1       0
Bank Sta=157,186.5
XS Rating Curve= 0 ,0
Exp/Cntr=0.3,0.1

Type RM Length L Ch R = 1 ,1030.7  ,44.9,45,45
XS GIS Cut Line= 2
     1867459.431      493039.338     1867791.002      493001.781
#Sta/Elev= 23
       0  806.69    19.6  793.18    39.3  779.74    58.9  766.07    78.5  752.23
    88.3  746.54    98.1  744.53     108  744.39   117.8  743.41   127.6  741.58
   137.4  739.24   147.2  736.21     157   734.8   166.8  734.69   176.7  736.07
   196.3  742.98   206.1  745.54   215.9  747.25   225.7  748.44   235.6  749.23
   245.4  749.76   274.8  751.14   333.7  754.32
#Mann= 3 , 0 , 0
       0      .1       0   147.2    .045       0   176.7      .1       0
Bank Sta=147.2,176.7
XS Rating Curve= 0 ,0
Exp/Cntr=0.3,0.1

Type RM Length L Ch R = 1 ,985.7   ,164.4,146.7,129
XS GIS Cut Line= 2
     1867473.897       493082.18     1867805.468      493044.623
#Sta/Elev= 26
       0  811.77    19.6  798.15    29.4  791.25    78.5  756.38    88.3  749.75
    98.1  745.18     108  743.55   117.8  742.78   127.6  741.11   139.8  737.84
   147.2  735.81     157   734.8   166.8  736.24   169.8  737.21   176.7  739.45
   186.5  741.84   196.3  743.18   215.9  744.58   225.7  746.83   235.6  750.06
   245.4  752.06   255.2  753.31     265  754.22   314.1  757.09   323.9  757.51
   333.7  757.69
#Mann= 3 , 0 , 0
       0      .1       0   139.8    .045       0   169.8      .1       0
Bank Sta=139.8,169.8
XS Rating Curve= 0 ,0
Exp/Cntr=0.3,0.1

Type RM Length L Ch R = 1 ,839     ,260.8,275.4,289.2
XS GIS Cut Line= 2
     1867538.859      493323.343      1867798.23       493105.75
#Sta/Elev= 26
       0  833.51     9.7  830.68    19.4  829.01      29  828.55    38.7  828.98
    48.4  827.87      58  823.41    67.7  816.47    87.1   801.9   135.4  765.08
   145.1  757.82   154.8  751.24   164.4  747.17   183.8  737.26   193.5  734.65
   203.1  734.65   212.8  736.12   222.5  739.39   232.2  742.44   241.8  744.67
   270.8  750.63   299.9  756.47   309.5  757.95   319.2  758.13   328.9  757.56
   338.6   757.3
#Mann= 3 , 0 , 0
       0      .1       0   183.8    .045       0   212.8      .1       0
Bank Sta=183.8,212.8
XS Rating Curve= 0 ,0
Exp/Cntr=0.3,0.1

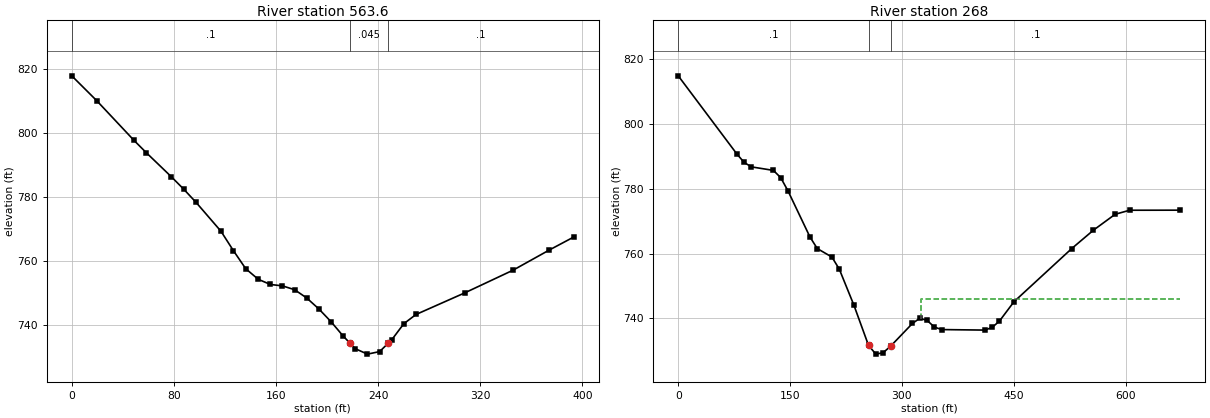
Type RM Length L Ch R = 1 ,563.6   ,290.1,295.6,300.8
XS GIS Cut Line= 3
     1867633.339      493386.582     1867772.923      493429.637
     1868013.895      493374.082
#Sta/Elev= 30
       0  817.87    19.5  810.12    48.7  797.71    58.4  793.84    77.9  786.36
    87.6  782.48    97.4   778.3   116.9  769.28   126.6  763.24   136.3  757.57
   146.1  754.26   155.6  752.64   165.1   752.2   174.6     751   184.1  748.41
   193.6  744.99   203.1  741.02   212.6  736.54   217.9  734.33   222.2  732.54
   231.7  730.86   241.2  731.65   247.9  734.25   250.7  735.34   260.2  740.38
   269.7  743.25   307.8  749.99   345.8  757.11   374.3  763.44   393.4  767.49
#Mann= 3 , 0 , 0
       0      .1       0   217.9    .045       0   247.9      .1       0
Bank Sta=217.9,247.9
XS Rating Curve= 0 ,0
Exp/Cntr=0.3,0.1

Type RM Length L Ch R = 1 ,268     ,279.7,268,255.6
XS GIS Cut Line= 3
     1867591.505      493718.268     1867924.854      493701.915
     1868189.607      493489.199
#Sta/Elev= 30
       0  814.93    78.5  790.81    88.4  788.15    98.2  786.78   127.6   785.7
   137.4  783.47   147.2  779.36   176.7   765.1   186.5  761.53   206.1  758.91
     216  755.18   235.6  744.04   255.2  731.61     265   728.9   274.8  729.34
   284.7  731.32   314.1  738.38   323.9  739.98   333.8  739.33   343.4  737.29
   353.2  736.49   411.4  736.33   421.1  737.17   430.8  739.11   450.2  745.07
   527.8  761.54   556.9  767.22     586  772.13   605.4  773.38   673.4   773.4
#Mann= 3 , 0 , 0
       0      .1       0   255.2    .045       0   284.7      .1       0
#XS Ineff= 2 , 0
                             325          745.97
Permanent Ineff=
       F       F
Bank Sta=255.2,284.7
XS Rating Curve= 0 ,0
Exp/Cntr=0.3,0.1

Chan Stop Cuts=-1
Use User Specified Reach Order=0
Composite Channel Slope=5